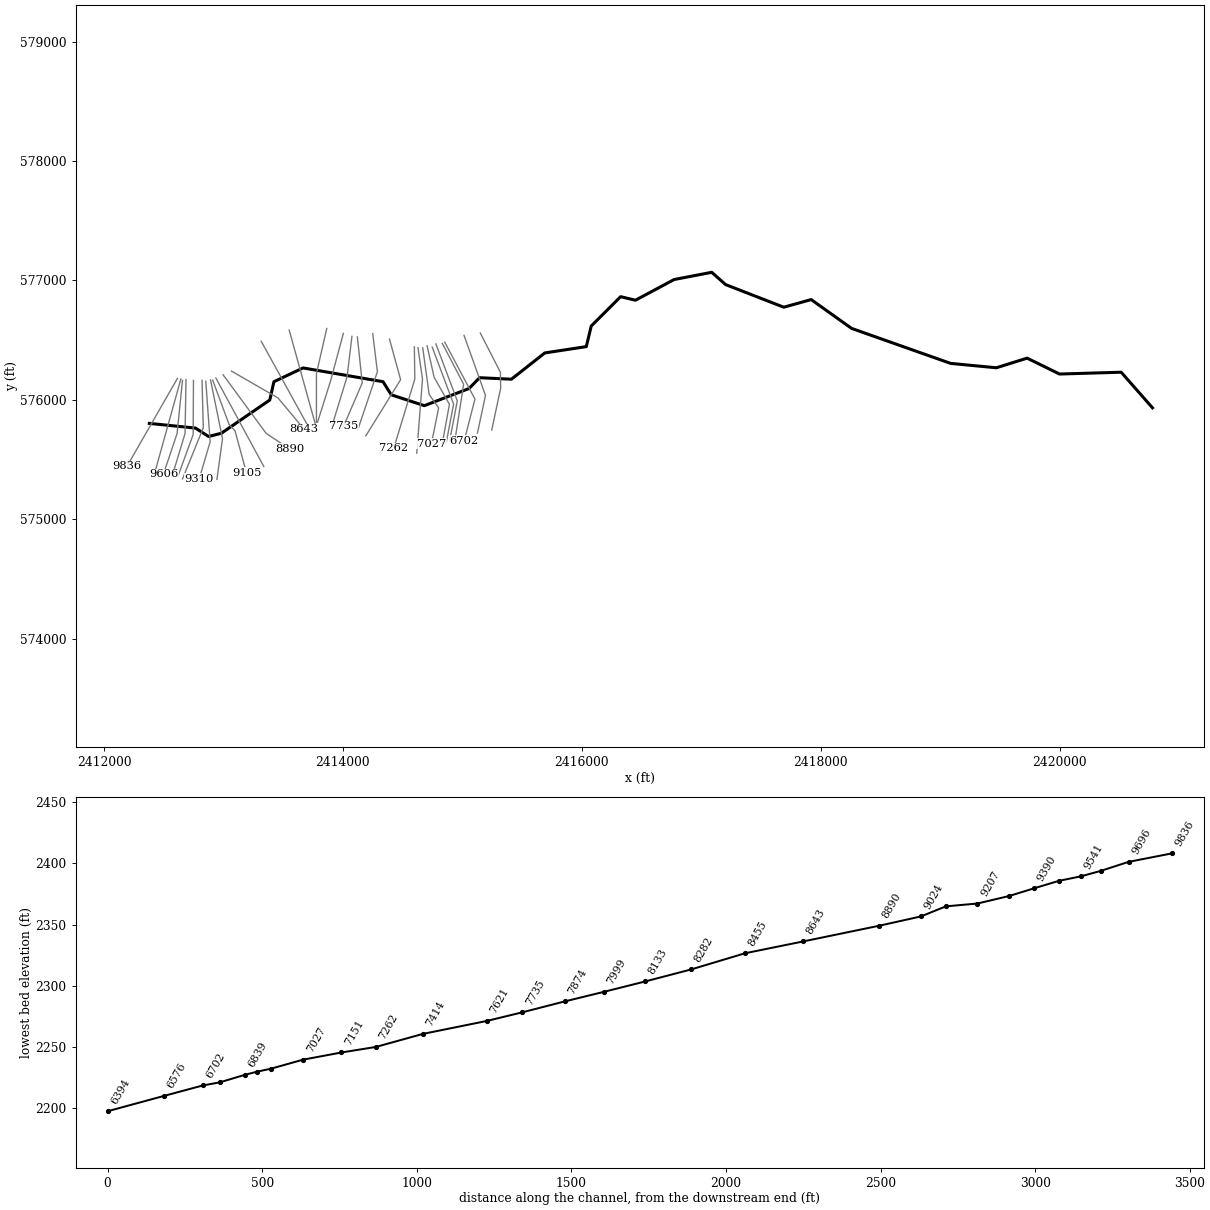
--- MOYERRN.prj (project) ---

Proj Title=MOYERRN
Current Plan=p01
Default Exp/Contr=0,0
English Units
Geom File=g01
Flow File=f01
Plan File=p01
BEGIN DESCRIPTION:
Stream Name: Moyer Run
Flood Zone: Approximate
Pendleton County, West Virginia
HEC-RAS Version: 5.0.7
Hydrology Method:
Regression
Model Notes:
NA
END DESCRIPTION:
DSS Export Rating Curves= 0
DSS Export Rating Curve Sorted= 0
DSS Export Volume Flow Curves= 0
DXF OffsetX= 0
DXF OffsetY= 0
DXF ScaleX= 0
DXF ScaleY= 0

--- MOYERRN.p01 (plan) ---

Plan Title=Floodplain
Program Version=4.00
Geom File=g01
Flow File=f01
K Sum by GR=0
Std Step Tol=0.01
Critical Tol=0.01
Num of Std Step Trials=20
Max Error Tol=0.3
Flow Tol Ratio=0.001
Split Flow NTrial=30
Split Flow Tol=0.02
Split Flow Ratio=0.02
Log Output Level=0
Friction Slope Method=1
Unsteady Friction Slope Method=2
Unsteady Bridges Friction Slope Method=1
Global Log Level=0
CheckData=False
Run HTab=0
Run UNet=0
Run PostProcess=0
UNET Theta=0
UNET Theta Warmup=0
UNET ZTol=0
UNET ZSATol=0
UNET MxIter=0
UNET MaxInSteps=0
UNET DtIC=0
UNET DtMin=0
UNET MaxCRTS=0
UNET WFStab=0
UNET SFStab=0
UNET WFX=0
UNET SFX=0
UNET DSS MLevel=0
UNET DZMax Abort=0
UNET Convert EG Bridges=0
UNET Use Existing IB Tables=0
UNET Froude Limit=0
UNET Froude Power=0
Write IC File=0
Echo Input=False
Echo Output=False
Write Detailed=0

--- MOYERRN.f01 (steady flow) ---

Flow Title=Flows
Program Version=5.07
Number of Profiles= 6
Profile Names=P100yr,P10yr,P25yr,P50yr,P500yr,P101yr
River Rch & RM=MOYERRN,Main            ,9836
     556     260     367     459     814     676
River Rch & RM=MOYERRN,Main            ,7999
     646     302     427     533     948     786
River Rch & RM=MOYERRN,Main            ,4037
     837     390     552     690    1232    1019
River Rch & RM=MOYERRN,Main            ,3493
     931     432     613     767    1371    1133
Boundary for River Rch & Prof#=MOYERRN,Main            , 1
Up Type= 0
Dn Type= 3
Dn Slope=0.05
Boundary for River Rch & Prof#=MOYERRN,Main            , 2
Up Type= 0
Dn Type= 3
Dn Slope=0.05
Boundary for River Rch & Prof#=MOYERRN,Main            , 3
Up Type= 0
Dn Type= 3
Dn Slope=0.05
Boundary for River Rch & Prof#=MOYERRN,Main            , 4
Up Type= 0
Dn Type= 3
Dn Slope=0.05
Boundary for River Rch & Prof#=MOYERRN,Main            , 5
Up Type= 0
Dn Type= 3
Dn Slope=0.05
Boundary for River Rch & Prof#=MOYERRN,Main            , 6
Up Type= 0
Dn Type= 3
Dn Slope=0.05
DSS Import GetInterval= 0
DSS Import GetPeak= 0
DSS Import FillOption= 0

--- MOYERRN.g01 (geometry) ---

Geom Title=Geometry
Program Version=5.07

River Reach=MOYERRN         ,Main
Reach XY= 30
     2412379.623575802.7090000212412765.38100001575763.621000022
2412875.65500003575693.0780000092412982.50700003575720.072999999
2413387.96300003575998.6570000052413422.36200002576151.989999995
2413666.34099999576267.292000011     2414336.044 576151.99500002
     2414404.458576042.272000015     2414681.523575951.369000003
2415055.69499999576094.910999998     2415143.873 576185.54900001
     2415410.329576172.7900000212415689.91700003576393.069000006
      2416037.34576445.9150000212416078.64800003576618.709999993
     2416324.662576864.415000007     2416448.655576834.677000016
2416772.69200003577008.0949999992417087.24000001 577068.47300002
2417203.31400001576965.5520000012417690.23100001576776.131999999
2417919.64900002576839.986000001      2418257.78      576598.603
2419086.68100002576305.419000015     2419469.495576268.658999994
2419727.03999999576349.4590000062419998.69299999576216.233999997
2420514.54200003576231.5160000032420776.77998433575933.011930853

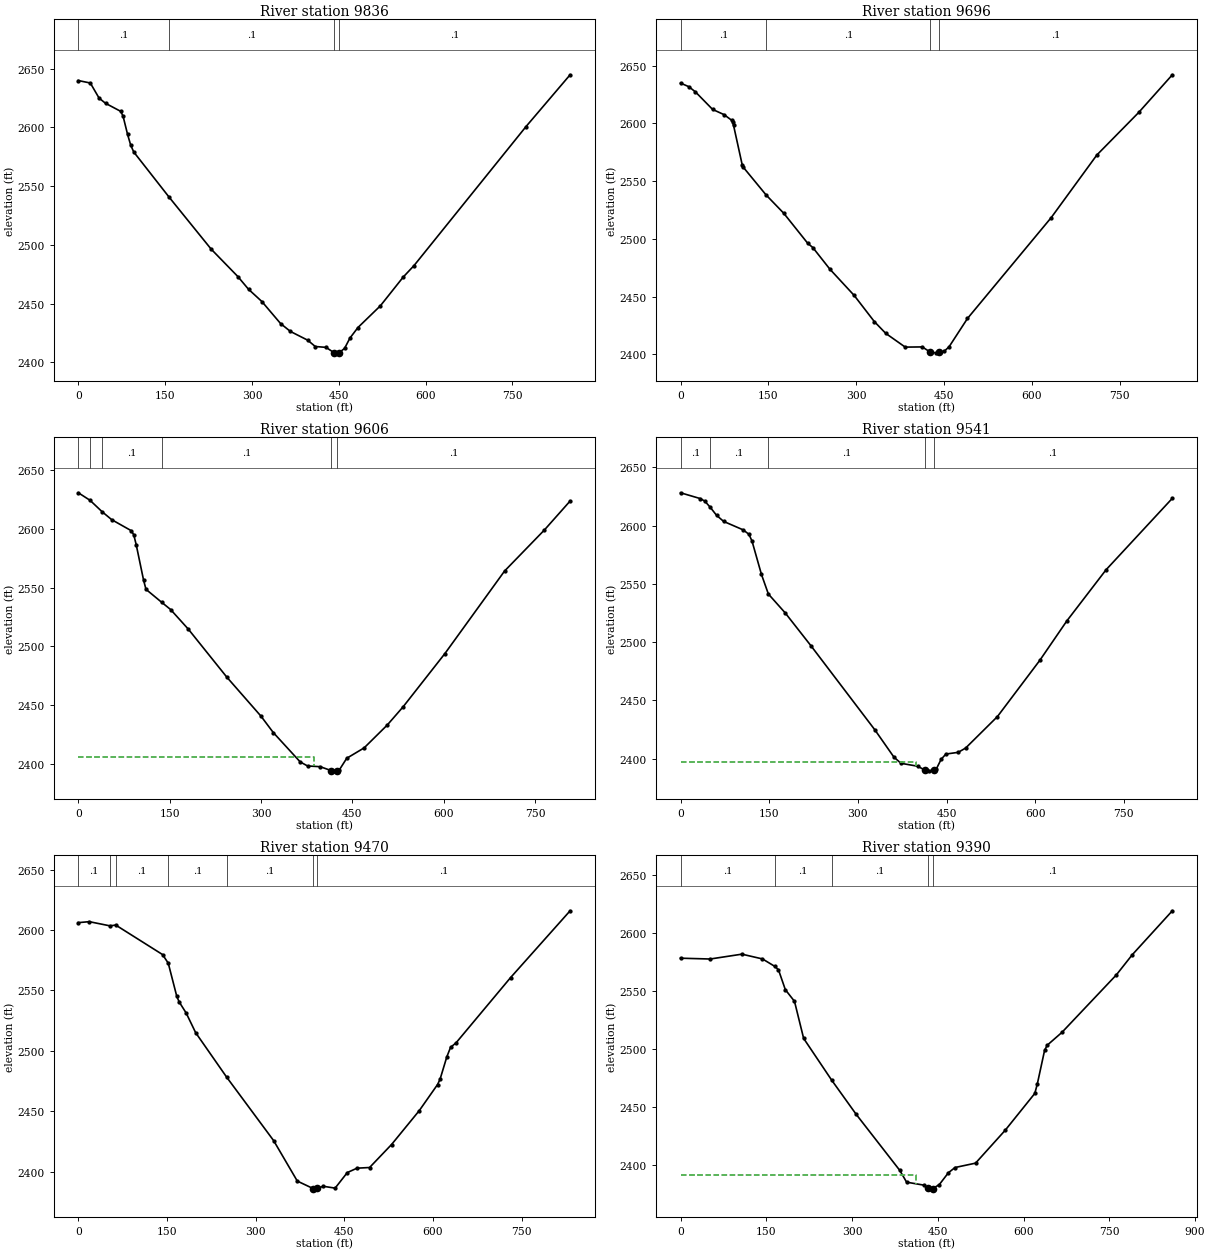
Type RM Length L Ch R = 1 ,9836    ,140.1,140.1,140.1
XS GIS Cut Line= 2
2412614.70021407576179.7081328092412192.21421407 575442.63713281
#Sta/Elev= 30
       0 2639.82    20.7 2637.73    35.9 2624.87      47 2620.47    73.4 2613.58
    77.4 2609.32    85.1 2593.99    90.6 2584.71    95.8 2579.02  156.692540.727
   229.5 2496.42   275.6  2473.1     294  2462.3   317.1 2451.86   349.4 2433.13
   366.4 2426.41   396.3 2418.96   409.3  2413.6     428 2412.86   441.6 2408.37
   446.2 2408.21   450.8 2408.42     460 2412.03   469.2 2420.75   483.1 2429.76
   521.8 2448.21   561.4 2472.74   579.9 2482.42   773.5 2600.73   849.6 2644.73
#Mann= 4 ,-1 , 0
       0      .1       0  156.69      .1       0   441.6    .045       0
   450.8      .1       0
Bank Sta=441.6,450.8
XS Rating Curve= 0 ,0
Exp/Cntr=0.3,0.1

Type RM Length L Ch R = 1 ,9696    ,87.8,90.1,92
XS GIS Cut Line= 2
     2412643.369       576174.22     2412418.347      575365.241
#Sta/Elev= 30
       0 2634.83    14.2 2631.68    25.5 2627.16    54.7 2612.03    74.2 2607.53
    87.2 2602.67    88.9 2601.49    90.5 2598.23   105.5 2563.56   106.7 2562.23
  146.272537.849   176.1  2522.2   217.1 2496.16   225.9 2492.41   254.9 2473.77
   296.5 2450.96   330.8 2428.39   350.4 2418.13   383.6 2406.25   412.7 2406.42
   426.72401.815   436.9 2401.29   441.72401.662   450.1 2402.65   458.4 2406.46
   489.9 2431.04   632.9 2518.38   710.8 2572.56   782.2 2609.36   839.7 2642.01
#Mann= 4 ,-1 , 0
       0      .1       0  146.27      .1       0   426.7    .045       0
   441.7      .1       0
Bank Sta=426.7,441.7
XS Rating Curve= 0 ,0
Exp/Cntr=0.3,0.1

Type RM Length L Ch R = 1 ,9606    ,64.2,65,65.6
XS GIS Cut Line= 3
2412657.14643727576163.0961051422412611.84474156575717.629430658
2412497.33212185575376.608332395
#Sta/Elev= 30
       0 2630.98   19.212624.573   38.922614.891    54.8 2608.06      87 2598.63
      91 2595.18      95 2586.83   107.1 2556.58   111.1 2548.66  136.582537.722
   151.5 2531.45   180.7 2514.66   243.7 2473.86     300 2440.46   320.1 2426.54
   364.3  2401.5   376.4 2398.04   397.2 2397.43   415.1 2394.11   420.6 2393.89
   424.7 2394.13   428.7  2394.8   440.7  2404.6   469.3 2413.47   507.2 2432.92
   533.2 2448.43   601.9 2493.89   699.9 2564.28   765.3 2599.27   807.5 2623.96
#Mann= 6 ,-1 , 0
       0      .1       0   19.21      .1       0   38.92      .1       0
  136.58      .1       0   415.1    .045       0   424.7      .1       0
#XS Ineff= 2 , 0
          386.86 2405.65
Permanent Ineff=
       F       F
Bank Sta=415.1,424.7
XS Rating Curve= 0 ,0
Exp/Cntr(USF)=0,0
Exp/Cntr=0.3,0.1

Type RM Length L Ch R = 1 ,9541    ,68.8,70.4,71.2
XS GIS Cut Line= 3
     2412686.445      576169.4382412678.70738044575718.487869527
2412568.56941294575353.837945673
#Sta/Elev= 30
       0 2628.18    33.1 2623.24    40.9 2621.07    50.12615.807    60.9 2608.83
    72.9 2603.59   105.9 2596.34   115.7 2592.52   120.9 2586.67   136.9 2558.01
  148.552541.254   176.9 2525.11   220.9 2496.61   328.9 2424.46   360.9 2401.21
   372.9 2395.88   400.9 2393.39   412.9 2390.17   420.9 2389.41   428.12389.997
   432.9 2391.27   440.9 2399.39   448.9 2403.83   469.7 2405.29   482.3 2409.01
     536    2436   607.8 2484.36   653.5 2518.21   719.7 2562.01   831.9 2623.44
#Mann= 5 ,-1 , 0
       0      .1       0    50.1      .1       0  148.55      .1       0
   412.9    .045       0   428.1      .1       0
#XS Ineff= 2 , 0
          397.68 2396.66
Permanent Ineff=
       F       F
Bank Sta=412.9,428.1
XS Rating Curve= 0 ,0
Exp/Cntr=0.3,0.1

Type RM Length L Ch R = 1 ,9470    ,82.1,79.8,76
XS GIS Cut Line= 3
2412749.00820913576163.0961051422412746.49144825575708.820767603
2412616.87826331575353.957484539
#Sta/Elev= 30
       0 2606.04    18.5 2606.84   53.562603.373   63.272604.034   142.5 2579.62
  152.172572.494   166.5 2545.21   170.5 2540.55   182.5 2531.21   198.5 2515.01
  250.792478.302   330.5 2425.64   370.5 2392.19   397.3 2385.99   398.5 2385.76
   403.6 2386.07   414.5 2387.88   434.5 2386.35   455.1 2399.22   471.5 2402.85
   492.8 2403.41     530 2422.45   576.8 2450.44   607.8 2472.06     612 2476.39
   623.5 2494.99   629.8 2502.84   639.1 2506.57   731.3 2560.53   832.1 2615.85
#Mann= 7 ,-1 , 0
       0      .1       0   53.56      .1       0   63.27      .1       0
  152.17      .1       0  250.79      .1       0   397.3    .045       0
   403.6      .1       0
Bank Sta=397.3,403.6
XS Rating Curve= 0 ,0
Exp/Cntr(USF)=0,0
Exp/Cntr=0.3,0.1

Type RM Length L Ch R = 1 ,9390    ,76.5,80.4,84.6
XS GIS Cut Line= 3
     2412820.744       576163.852412831.24256094575765.925295324
2412657.39987811575337.773668283
#Sta/Elev= 30
       0 2578.22    51.8 2577.52   107.3 2581.69   143.3 2577.59  164.942571.151
   171.3 2568.21   183.3 2551.11   199.3 2541.09   215.3 2509.18  264.072473.434
   307.3 2443.75   383.4  2395.6   395.4 2385.42   425.4 2382.88   433.32380.025
   438.3 2379.68   441.1 2379.94   452.5 2383.28   468.5 2393.53   480.1 2398.04
     516  2401.8   567.8 2430.08   619.6  2461.8   623.9  2469.7   636.7  2498.8
   641.2 2503.25   667.1 2514.37   762.1 2563.77   790.2 2581.25   860.2 2619.04
#Mann= 5 ,-1 , 0
       0      .1       0  164.94      .1       0  264.07      .1       0
   433.3    .045       0   441.1      .1       0
#XS Ineff= 2 , 0
          412.01 2391.89
Permanent Ineff=
       F       F
Bank Sta=433.3,441.1
XS Rating Curve= 0 ,0
Exp/Cntr=0.3,0.1

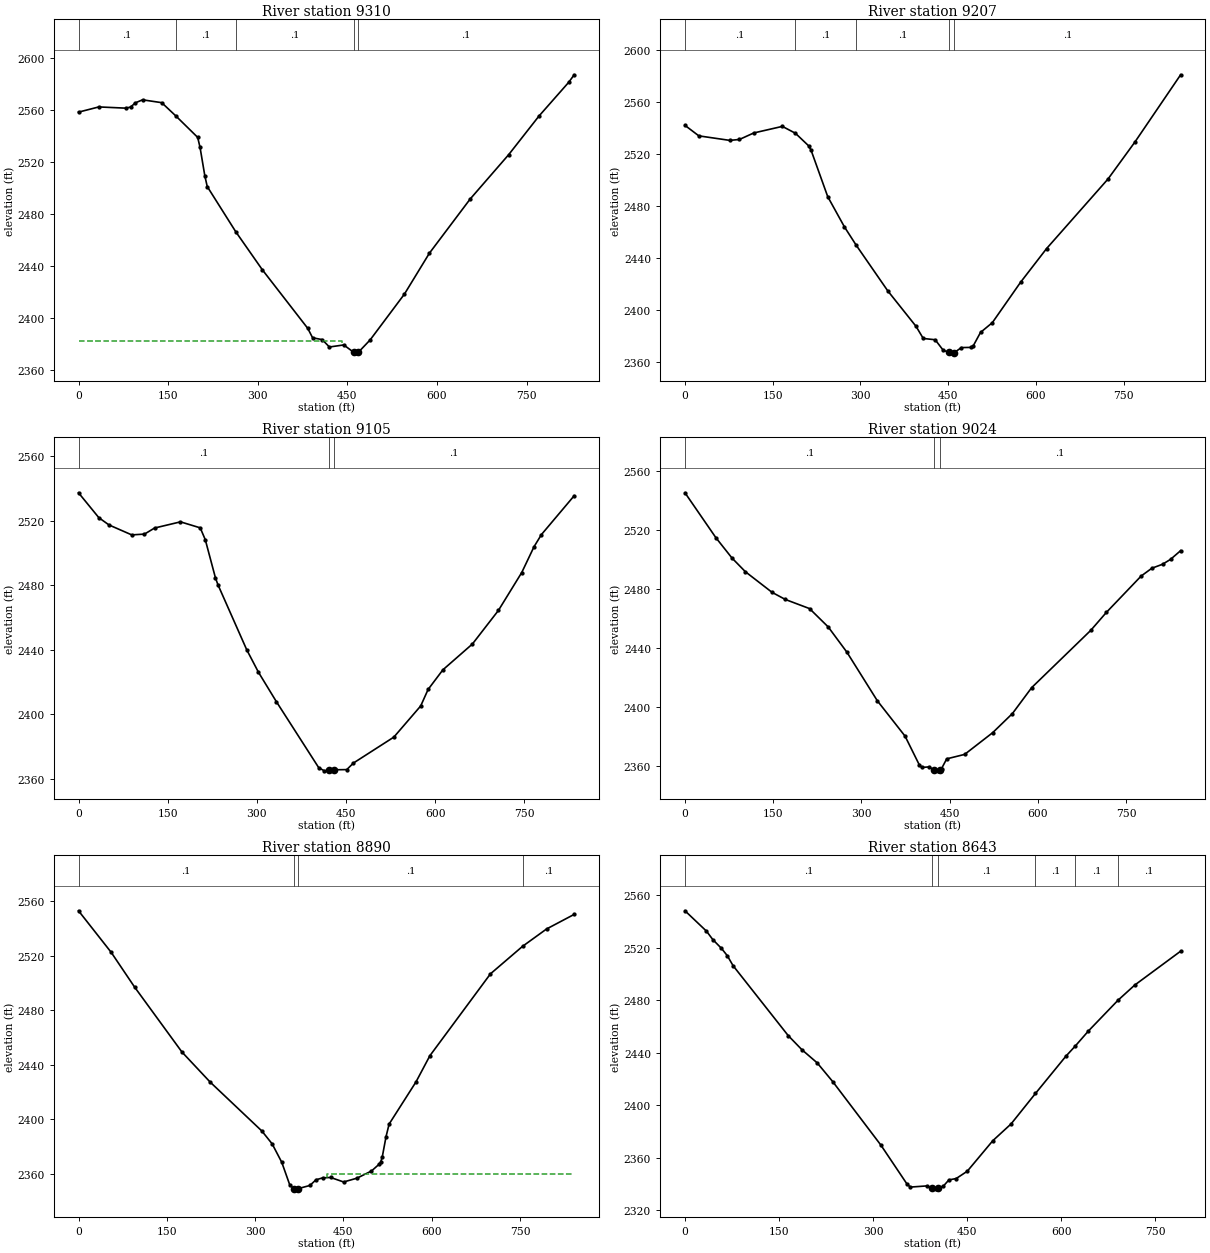
Type RM Length L Ch R = 1 ,9310    ,101.9,102.8,104.1
XS GIS Cut Line= 3
2412852.19540491576155.5458225242412888.68843757575648.418506656
2412798.08504615575340.115299739
#Sta/Elev= 30
       0 2558.63      34 2562.64    79.2  2561.7    87.2 2562.55    95.2 2565.79
   107.2 2568.11   139.3 2565.92  163.022555.673   199.5 2539.22   203.5 2531.44
   211.5 2509.56   215.5 2501.38   263.12466.708   307.7 2437.36   383.9 2392.18
   391.9 2384.97     408  2383.6     420  2377.9   444.1 2379.49   460.5 2373.88
   464.1 2373.41   468.3 2373.75   488.2 2383.34   545.7 2418.66   587.4 2450.07
   655.7 2491.78   720.2 2525.93   770.8 2555.57   820.9 2581.72   829.8 2587.38
#Mann= 5 ,-1 , 0
       0      .1       0  163.02      .1       0   263.1      .1       0
   460.5    .045       0   468.3      .1       0
#XS Ineff= 2 , 0
          440.91 2382.15
Permanent Ineff=
       F       F
Bank Sta=460.5,468.3
XS Rating Curve= 0 ,0
Exp/Cntr(USF)=0,0
Exp/Cntr=0.3,0.1

Type RM Length L Ch R = 1 ,9207    ,96.8,102.4,107.2
XS GIS Cut Line= 3
2412891.62967798576167.7621121892412992.13257064575675.711097642
2412945.56618074575333.546224377
#Sta/Elev= 30
       0 2542.36    23.7 2534.27    76.7 2530.79    93.1  2531.5   117.6 2536.51
   166.5 2541.57  188.822536.286   211.4 2526.63   215.5 2523.36   244.1 2487.45
   272.7 2464.16  292.862450.036   346.7 2414.98   395.1 2387.62   407.4 2378.31
   427.8 2377.32   441.6  2369.2   451.8 2367.57   456.4 2367.24   460.5 2367.46
   472.7 2371.29   489.5 2371.43   493.1  2372.8   505.3 2382.94   525.5 2390.45
   573.9 2421.62   618.3 2447.51   723.3 2501.05   769.2 2529.45   847.5  2581.3
#Mann= 5 ,-1 , 0
       0      .1       0  188.82      .1       0  292.86      .1       0
   451.8    .045       0   460.5      .1       0
Bank Sta=451.8,460.5
XS Rating Curve= 0 ,0
Exp/Cntr=0.3,0.1

Type RM Length L Ch R = 1 ,9105    ,83.5,81.1,78.9
XS GIS Cut Line= 4
2412910.07067641576164.6542620132413046.78361272575794.907911559
2413096.71947304 575740.726865992413193.04220355575387.543520803
#Sta/Elev= 30
       0 2537.37    34.2 2521.93    51.3 2517.41    89.6 2511.25     111 2511.74
     128 2515.51   171.6 2519.34   204.8 2515.62   213.3 2508.28   230.4 2484.61
   234.6 2480.33     283 2440.03   302.8 2426.04   332.8 2407.89   404.2 2366.85
   413.6  2364.9   420.82365.144   430.32365.558   451.4 2365.66   462.6 2369.74
   530.6 2385.82   575.8 2405.16   588.2 2415.37   613.1 2427.55   662.8 2443.58
   706.5 2464.37   745.8 2487.91   766.5 2503.93   778.9 2511.44     834 2535.52
#Mann= 3 , 0 , 0
       0      .1       0   420.8    .045       0   430.3      .1       0
Bank Sta=420.8,430.3
XS Rating Curve= 0 ,0
Exp/Cntr(USF)=0,0
Exp/Cntr=0.3,0.1

Type RM Length L Ch R = 1 ,9024    ,131.5,134.2,135.1
XS GIS Cut Line= 2
2412936.46790236576182.8751121892413337.66979017575441.590780471
#Sta/Elev= 30
       0  2545.1    52.6 2514.63    79.9 2500.89   102.7  2491.6   148.1 2477.61
   170.7 2472.78   211.8 2466.61   243.6 2454.16   275.5 2436.98   327.1 2404.13
   374.3 2380.13   398.3 2360.82   402.8  2358.9   415.6 2359.34   423.12357.063
   430.1 2356.63   433.3 2357.08   436.3 2358.14   445.1 2364.75   475.6 2367.77
   523.3 2382.51   556.9 2395.48   589.7 2413.08   690.1 2451.86   716.6 2464.01
   775.7 2488.64   793.9 2493.95   812.1 2496.65   825.8 2499.99   842.9 2505.87
#Mann= 3 ,-1 , 0
       0      .1       0   423.1    .045       0   433.3      .1       0
Bank Sta=423.1,433.3
XS Rating Curve= 0 ,0
Exp/Cntr=0.3,0.1

Type RM Length L Ch R = 1 ,8890    ,242.8,246.4,250.3
XS GIS Cut Line= 3
2412997.22743549576209.8240552092413357.65244937575718.900329406
2413551.84696116575589.955173578
#Sta/Elev= 30
       0 2552.87    55.5 2522.42    95.2    2497   175.7 2449.37   223.6 2427.35
   311.5 2391.47     329 2382.03   345.3 2368.55   358.8  2352.1   365.5 2349.27
   368.7 2349.08   373.7 2349.29   393.1 2351.55   403.5 2355.72   414.8 2357.11
   428.3 2357.42   450.4 2354.11   472.9 2356.87   497.7 2362.13   510.4 2366.99
   513.3 2368.49   516.2 2372.75   522.5 2387.38   527.7 2396.55   573.4 2427.47
     597 2446.66   699.9 2506.66  754.412526.806   795.2 2539.53   842.1 2550.22
#Mann= 4 ,-1 , 0
       0      .1       0   365.5    .045       0   373.7      .1       0
  754.41      .1       0
#XS Ineff= 2 , 0
                          421.65            2360
Permanent Ineff=
       F       F
Bank Sta=365.5,373.7
XS Rating Curve= 0 ,0
Exp/Cntr(USF)=0,0
Exp/Cntr=0.3,0.1

Type RM Length L Ch R = 1 ,8643    ,192.9,187.7,184
XS GIS Cut Line= 3
2413067.13745974576240.8951770962413457.08003941 576015.62954342
2413674.57789261575754.632119576
#Sta/Elev= 30
       0 2548.27    34.2 2532.76    44.4 2526.29    58.2 2519.58    67.5 2513.99
    76.7 2506.38   164.5 2453.11   186.5 2442.26   210.7 2432.31   235.5    2418
   312.4 2369.48   353.9 2339.88   359.2 2337.55   386.2 2338.46   394.3 2336.63
     400 2336.21   403.1 2336.53   411.9 2338.33   420.7    2343   432.4 2344.09
     450 2349.64   490.7 2372.92   519.8 2385.71  558.66 2408.93   607.2 2437.36
  622.082445.075   643.1 2456.59  690.232480.016   716.9 2491.59   790.1 2517.45
#Mann= 6 ,-1 , 0
       0      .1       0   394.3    .045       0   403.1      .1       0
  558.66      .1       0  622.08      .1       0  690.23      .1       0
Bank Sta=394.3,403.1
XS Rating Curve= 0 ,0
Exp/Cntr(USF)=0,0
Exp/Cntr=0.3,0.1

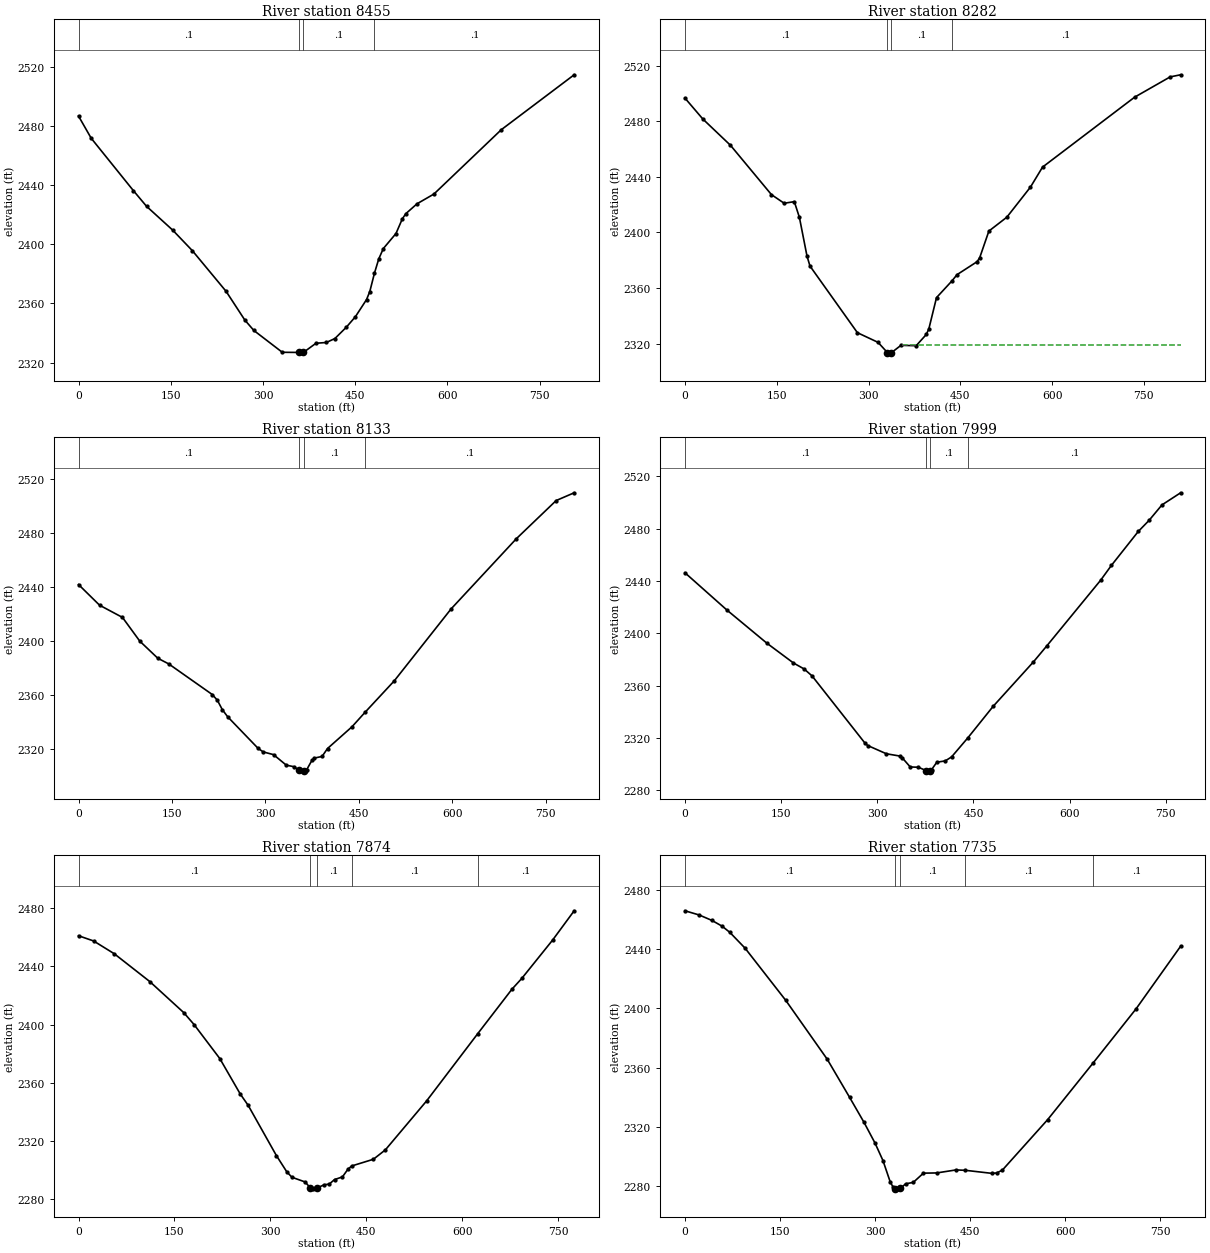
Type RM Length L Ch R = 1 ,8455    ,175.8,173.7,172
XS GIS Cut Line= 2
2413316.12838833576490.7108330022413705.47639715575784.897693857
#Sta/Elev= 30
       0 2486.62    20.7 2471.58    89.3 2436.18   110.6 2425.63   153.2  2409.5
   185.2  2395.6     240 2368.14   270.5 2348.71   285.2 2341.67   331.4 2326.93
     359 2326.83   363.3 2326.56   365.92326.886   386.2 2333.04     403 2333.55
     417 2336.23   435.4 2343.81   450.2 2350.91   468.4 2362.54   473.7 2367.95
  481.342380.467   488.4 2390.18   495.8 2397.09   516.3 2407.21   526.6  2417.1
   532.3 2420.63   550.6 2427.33     578  2433.9   687.6 2477.39   806.1 2514.52
#Mann= 4 ,-1 , 0
       0      .1       0     359    .045       0   365.9      .1       0
  481.34      .1       0
Bank Sta=359,365.9
XS Rating Curve= 0 ,0
Exp/Cntr(USF)=0,0
Exp/Cntr=0.3,0.1

Type RM Length L Ch R = 1 ,8282    ,153.7,149.1,145.6
XS GIS Cut Line= 2
2413550.12078772576584.6913868562413766.85145273575804.077398725
#Sta/Elev= 30
       0 2496.66    29.2 2481.62    74.4  2462.7   141.3 2427.23   162.1 2421.01
   178.7 2422.17     187 2410.89   199.4 2383.07   204.3 2375.83   281.8 2327.88
   315.6 2320.91     331  2313.5   332.2 2313.38   337.5 2313.52     353 2318.78
   377.9 2318.52   394.5 2326.65   398.6 2330.65   411.1 2353.11  436.322365.128
   444.7 2369.65   477.5 2378.99   481.7 2381.84   496.7    2401     526 2410.96
   564.7 2432.67   584.4 2447.02   734.9 2497.34     793 2511.94   810.1 2513.46
#Mann= 4 ,-1 , 0
       0      .1       0     331    .045       0   337.5      .1       0
  436.32      .1       0
#XS Ineff= 2 , 0
                          354.47         2319.29
Permanent Ineff=
       F       F
Bank Sta=331,337.5
XS Rating Curve= 0 ,0
Exp/Cntr(USF)=0,0
Exp/Cntr=0.3,0.1

Type RM Length L Ch R = 1 ,8133    ,135.1,133.6,133.9
XS GIS Cut Line= 3
 2413864.7561742576597.7949612222413778.35927565576220.276994363
2413778.35927565575811.749280673
#Sta/Elev= 30
       0 2441.88    33.8 2426.52    70.6 2417.44    98.4 2399.82   127.3 2387.13
   144.9 2382.91   214.7  2360.2   222.9 2355.97   230.8 2349.03   239.3 2343.75
   288.5 2320.12   296.7 2317.55   313.1 2315.55   333.6 2307.73   345.9 2306.58
   354.4  2303.8   358.3 2303.51   362.4 2303.67   366.5 2304.48   374.7 2311.23
   378.8 2313.01     391 2314.19   399.8 2320.09     439  2336.2  460.612347.264
     507 2370.36   598.1 2423.71     703 2475.91   766.9 2504.24   795.8 2510.01
#Mann= 4 ,-1 , 0
       0      .1       0   354.4    .045       0   362.4      .1       0
  460.61      .1       0
Bank Sta=354.4,362.4
XS Rating Curve= 0 ,0
Exp/Cntr(USF)=0,0
Exp/Cntr=0.3,0.1

Type RM Length L Ch R = 1 ,7999    ,126.3,125.6,125
XS GIS Cut Line= 3
2414003.43311228576555.9908764912413897.16987543 576160.30013927
2413788.11023761575813.546419019
#Sta/Elev= 30
       0  2446.4    65.7  2417.8   127.8 2392.57   169.2 2377.46   185.8  2372.9
   198.2  2367.6     281 2316.07   285.1 2314.36   314.2 2308.06   334.9 2306.35
     339 2304.94   351.4 2297.98   363.9 2297.77   376.3 2295.22   380.4 2295.02
   381.5 2295.24   384.6 2295.89   392.9 2301.61     406 2302.62   415.9 2305.67
  441.512320.388   480.7  2344.3   543.6  2378.3   564.6 2390.62   648.5 2440.76
   665.2 2452.04   707.1 2477.97   723.9 2486.42   744.1 2498.29   773.2 2507.55
#Mann= 4 ,-1 , 0
       0      .1       0   376.3    .045       0   381.5      .1       0
  441.51      .1       0
Bank Sta=376.3,381.5
XS Rating Curve= 0 ,0
Exp/Cntr(USF)=0,0
Exp/Cntr=0.3,0.1

Type RM Length L Ch R = 1 ,7874    ,134.7,138.5,142.9
XS GIS Cut Line= 3
2414075.60961115 576531.982379152414034.99860873576194.292606303
      2413907.57      575778.175
#Sta/Elev= 30
       0 2461.01    23.6 2457.43    55.8 2448.69   111.4 2429.59   164.6 2408.24
   180.7 2400.07     221 2376.71   253.1 2352.29   265.3 2344.63   309.6 2310.04
   325.7    2299   333.8 2295.21   354.5 2291.98   362.8 2287.83     367 2287.26
   372.7 2287.77   384.4 2290.08   392.1 2290.48   400.5 2293.64   412.8 2295.45
   421.4 2300.71   427.22302.947   461.2 2307.55     480 2314.02   544.5 2347.63
  624.272393.674     678 2424.32   693.3 2431.68   741.5 2457.99   775.3 2478.15
#Mann= 5 ,-1 , 0
       0      .1       0   362.8    .045       0   372.7      .1       0
   427.2      .1       0  624.27      .1       0
Bank Sta=362.8,372.7
XS Rating Curve= 0 ,0
Exp/Cntr=0.3,0.1

Type RM Length L Ch R = 1 ,7735    ,118.4,114.5,110.6
XS GIS Cut Line= 3
2414121.01301212 576526.918978182414161.70080436576141.822983029
2414005.65517382575778.730608728
#Sta/Elev= 30
       0 2465.93    22.5 2463.08    42.6 2459.41    58.7 2455.51    70.8 2451.36
    94.9 2440.67     159 2405.51   224.5 2365.76   259.8 2340.05   282.7 2323.06
     300 2309.14   312.5 2297.37   324.1 2282.77   328.2  2279.7   332.2 2278.46
   336.2 2278.26   340.2 2278.57   348.3 2281.67   360.3 2282.59   376.4 2288.85
   397.3 2288.99   427.8 2291.02  442.79 2290.76   484.4 2288.71   491.9 2288.96
     501 2290.89   572.4 2324.92  644.192363.178     712 2399.71   782.4    2442
#Mann= 5 ,-1 , 0
       0      .1       0   332.2    .045       0   340.2      .1       0
  442.79      .1       0  644.19      .1       0
Bank Sta=332.2,340.2
XS Rating Curve= 0 ,0
Exp/Cntr=0.3,0.1

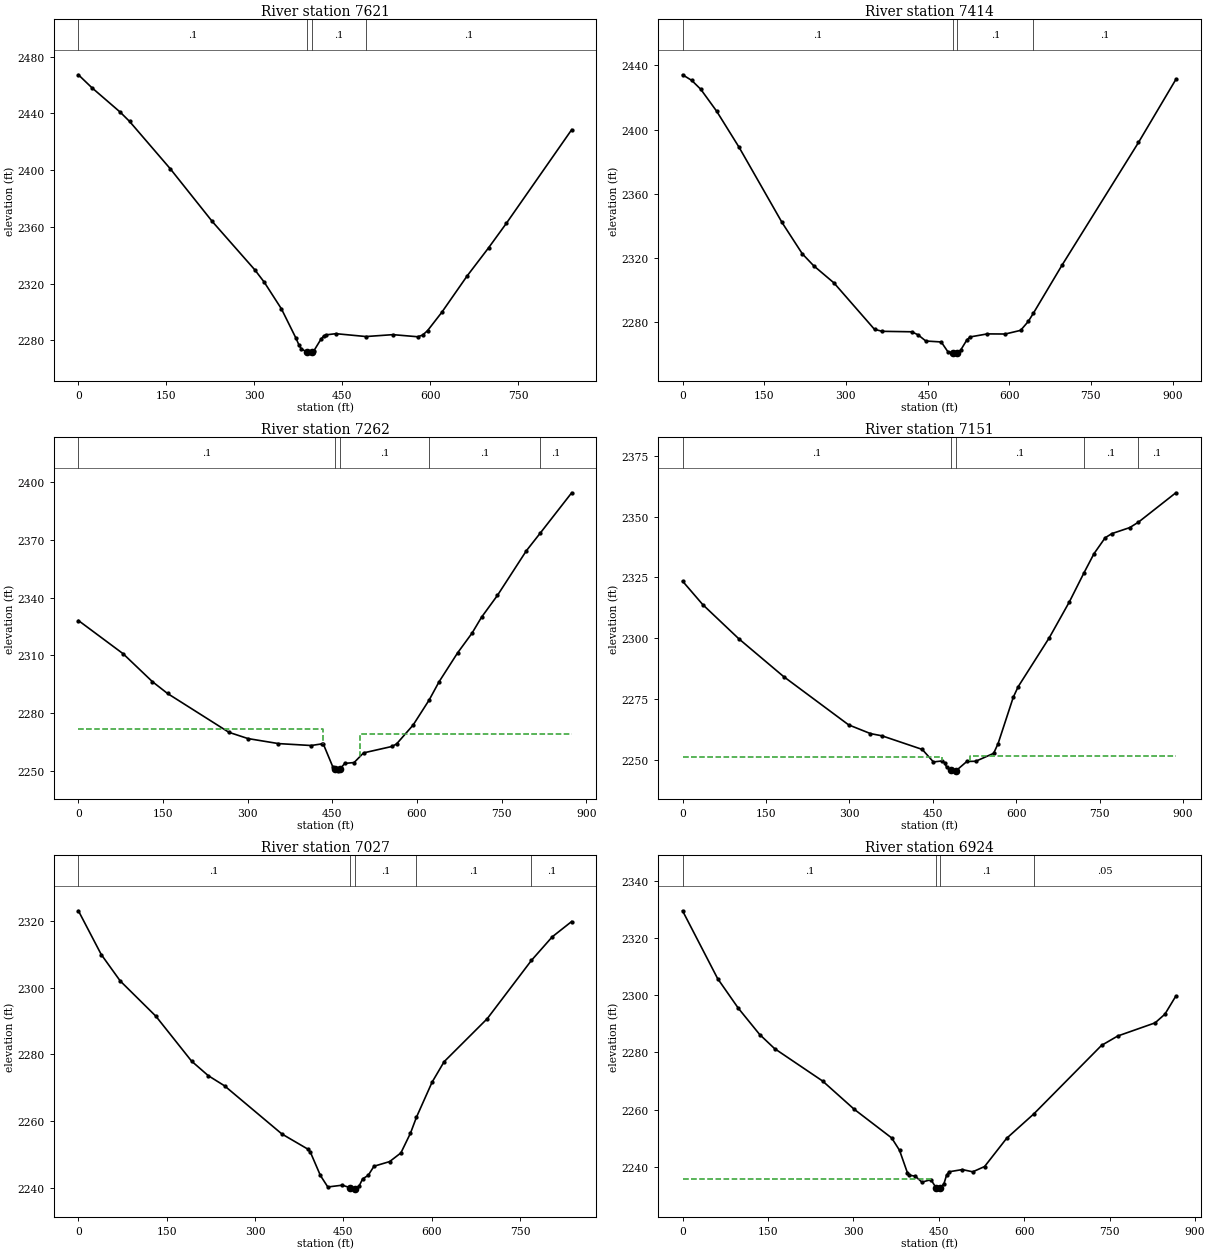
Type RM Length L Ch R = 1 ,7621    ,208.7,206.9,204.7
XS GIS Cut Line= 3
2414249.50994909576555.0926014552414288.66601119576235.802965453
     2414122.546       575743.74
#Sta/Elev= 30
       0 2467.18    22.7 2458.18    71.1 2440.92    87.2 2434.33   156.6 2400.96
   228.2 2363.81   300.8 2329.71   316.9 2320.99   346.2 2302.18     371  2281.5
   375.8 2276.96     380 2274.06   389.9 2271.68   396.2 2271.22   398.2  2271.6
   401.1 2272.41   413.7 2280.94     418 2282.91   422.2 2283.89   439.1 2284.72
  490.312282.705   536.2 2284.04   578.4 2282.56   586.8 2283.71   595.3 2286.87
   619.4 2299.69   662.8 2325.44   699.2 2345.17   729.6 2362.48     841 2428.48
#Mann= 4 ,-1 , 0
       0      .1       0   389.9    .045       0   398.2      .1       0
  490.31      .1       0
Bank Sta=389.9,398.2
XS Rating Curve= 0 ,0
Exp/Cntr=0.3,0.1

Type RM Length L Ch R = 1 ,7414    ,148.9,151.7,153.9
XS GIS Cut Line= 3
2414390.06772436 576508.823818912414483.01587859576168.689342179
2414191.55801212575698.297990302
#Sta/Elev= 30
       0 2434.16    16.9 2430.64    33.5 2425.09    62.5 2411.49     104 2388.81
   182.7 2341.97     220 2322.41   240.9 2314.96   278.1 2304.26   352.6 2275.25
   366.9 2274.05   420.7 2273.76   432.3 2271.92   446.8    2268   475.1 2267.41
   487.5 2261.22   496.2 2260.73   503.3 2260.62   504.9 2260.75   510.7 2262.26
   522.1 2268.62   528.2 2270.55   559.8 2272.44   592.7 2272.37   620.9 2274.65
     635 2280.23  644.092285.199   696.6 2315.13   837.4 2391.92     906 2431.24
#Mann= 4 ,-1 , 0
       0      .1       0   496.2    .045       0   504.9      .1       0
  644.09      .1       0
Bank Sta=496.2,504.9
XS Rating Curve= 0 ,0
Exp/Cntr=0.3,0.1

Type RM Length L Ch R = 1 ,7262    ,108.3,111.4,112.7
XS GIS Cut Line= 3
2414598.00998303 576443.710801942414601.86291981576174.282144118
2414426.10721018575595.764591757
#Sta/Elev= 30
       0 2328.15    79.2 2310.88   131.2 2296.33     158 2290.19   266.7 2270.01
   300.5 2266.75   354.5 2264.14   412.3 2263.14   431.5 2263.99   434.3  2263.7
   450.7 2252.12   453.9 2250.94   459.3 2249.97   463.5 2250.86   463.5 2250.87
   471.9 2253.82   488.6 2254.29   505.3  2259.3   555.5 2262.64   563.8 2263.96
   593.1 2273.77  621.452286.765   639.1 2296.28   671.9  2311.3   697.6 2321.61
   714.3 2329.83   742.5 2341.19   793.7 2364.38  818.452373.616   874.1 2394.57
#Mann= 5 ,-1 , 0
       0      .1       0   453.9    .045       0   463.5      .1       0
  621.45      .1       0  818.45      .1       0
#XS Ineff= 2 , 0
          433.83 2271.89  498.88         2269.22
Permanent Ineff=
       F       F
Bank Sta=453.9,463.5
XS Rating Curve= 0 ,0
Exp/Cntr=0.3,0.1

Type RM Length L Ch R = 1 ,7151    ,114.9,123.7,128.5
XS GIS Cut Line= 3
2414628.42957964576436.5064033942414666.18014211576172.883943634
     2414617.947      575553.851
#Sta/Elev= 30
       0 2323.47    36.3 2313.82     101  2299.8   181.8 2284.21   298.7 2264.35
     338 2260.76   358.9 2259.83   431.1 2254.25   451.2  2249.1   467.2 2249.52
   471.2 2248.79   475.2 2246.86   482.22245.581   490.6 2245.44     492  2245.5
   511.3  2249.3   527.4 2249.38   559.5 2252.64   567.5 2256.64   594.8  2275.7
   603.6 2280.04   659.8 2300.27   695.9 2315.03  722.172326.959     740 2334.76
   760.1 2341.31   772.1 2343.01   804.2 2345.48  819.982347.732   887.2 2359.81
#Mann= 5 ,-1 , 0
       0      .1       0   482.2    .045       0     492      .1       0
  722.17      .1       0  819.98      .1       0
#XS Ineff= 2 , 0
          466.26 2251.29  517.42         2251.64
Permanent Ineff=
       F       F
Bank Sta=482.2,492
XS Rating Curve= 0 ,0
Exp/Cntr=0.3,0.1

Type RM Length L Ch R = 1 ,7027    ,104.1,102.7,102.2
XS GIS Cut Line= 4
2414668.31761969576434.9762201552414721.82899628576044.861023135
2414801.23297443575932.659749656 2414740.8169041 575632.30557142
#Sta/Elev= 30
       0 2323.06    38.8 2309.93    71.1 2301.98   131.6 2291.41   192.2 2277.93
   220.5 2273.57   248.1 2270.53   345.6 2256.06     390 2251.48   394.1 2250.53
   410.9 2243.62   423.5 2240.16   448.2  2240.7   460.92239.962   468.3  2239.6
   470.12239.613   476.9 2240.52   482.6 2242.58   492.1 2243.65   501.9 2246.38
   528.5 2247.78   547.6 2250.38   563.9 2256.32   574.12261.129   600.6 2271.63
     621 2277.76   694.2 2290.67  769.352308.187   804.6 2315.24   837.6 2319.84
#Mann= 5 ,-1 , 0
       0      .1       0   460.9    .045       0   470.1      .1       0
   574.1      .1       0  769.35      .1       0
Bank Sta=460.9,470.1
XS Rating Curve= 0 ,0
Exp/Cntr(USF)=0,0
Exp/Cntr=0.3,0.1

Type RM Length L Ch R = 1 ,6924    ,49.1,47,45.9
XS GIS Cut Line= 4
2414704.77675088576452.7267073352414763.31714943576189.179963581
2414891.67017833575962.5669719332414831.41969754575632.230492304
#Sta/Elev= 30
       0 2329.47    61.6 2305.77    97.9 2295.42   135.4 2286.23   161.6  2281.3
     246 2269.96   301.3 2260.12   367.2 2250.08     381 2245.76   394.8 2237.93
   398.1 2237.05   408.6 2236.73   420.3 2234.62   436.1  2235.5   445.3 2232.64
   449.9 2232.29   452.7 2232.52   459.1 2234.14   463.7 2237.12   468.3 2238.26
   491.3 2239.02   509.6 2238.24   530.4 2240.09     569 2249.93  616.712258.462
   735.7 2282.42   764.1  2285.7   829.8  2290.3     847 2293.33   866.2 2299.66
#Mann= 4 ,-1 , 0
       0      .1       0   445.3    .045       0   452.7      .1       0
  616.71     .05       0
#XS Ineff= 2 , 0
          435.98  2235.9
Permanent Ineff=
       F       F
Bank Sta=445.3,452.7
XS Rating Curve= 0 ,0
Exp/Cntr=0.5,0.3

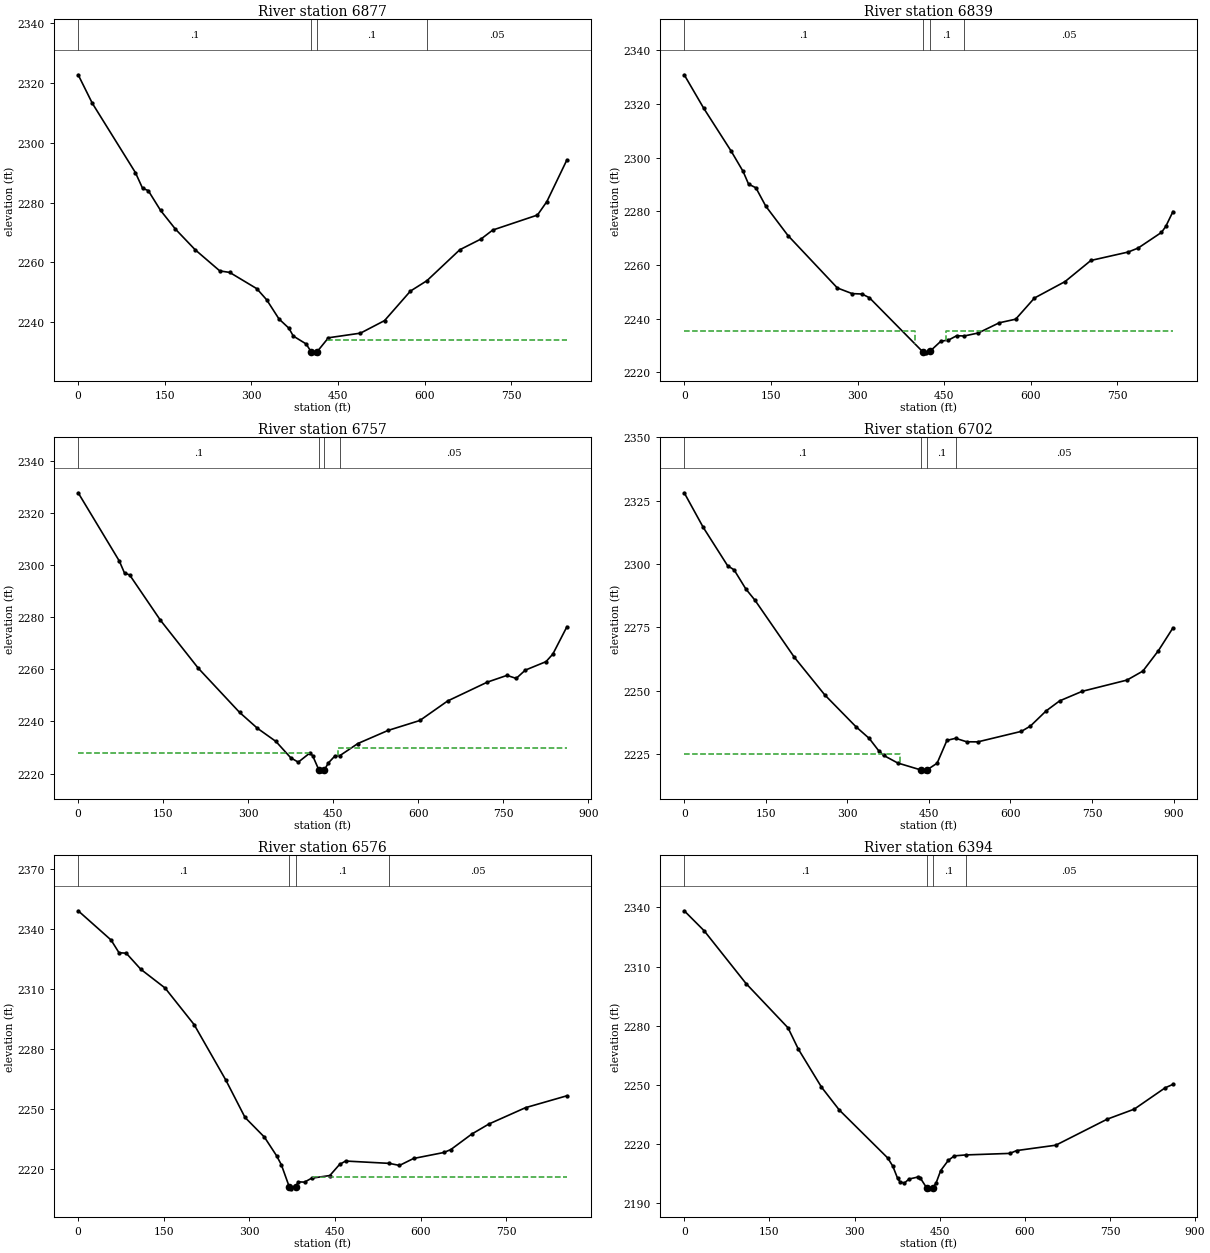
Type RM Length L Ch R = 1 ,6877    ,38.5,38.3,38.2
XS GIS Cut Line= 3
 2414747.4324539576442.1727659572414926.55569299575964.685040252
2414863.61799474 575634.48395432
#Sta/Elev= 30
       0 2322.77    24.5 2313.23    99.1 2290.03   111.5 2284.78   121.3 2284.01
   142.7 2277.36   168.3 2271.13   202.5 2264.21   245.2 2257.12   262.3 2256.62
   309.3 2251.17   326.4 2247.44   347.7 2241.03   364.8 2237.95   372.4 2235.32
   394.7 2232.67   403.5 2229.98   409.7  2229.7   412.8 2229.87   433.2 2234.74
   488.7 2236.29   530.4 2240.49   575.2 2250.37  603.762253.847   660.7 2264.21
   697.4  2267.8   717.7  2270.8   795.1 2275.82   811.4 2280.33   846.1 2294.28
#Mann= 4 ,-1 , 0
       0      .1       0   403.5    .045       0   412.8      .1       0
  603.76     .05       0
#XS Ineff= 2 , 0
             380    2234     430            2234
Permanent Ineff=
       F       F
Bank Sta=403.5,412.8
XS Rating Curve= 0 ,0
Exp/Cntr(USF)=0,0
Exp/Cntr=0.5,0.3

Type RM Length L Ch R = 1 ,6839    ,87.5,81.6,76.9
XS GIS Cut Line= 3
2414778.19286457 576468.738575172414957.31610366575991.250849465
2414894.37840541575661.049763533
#Sta/Elev= 30
       0 2330.93    33.7 2318.47    81.4 2302.41     102 2294.86   111.4 2290.15
   124.1 2288.78   141.2 2281.93   179.6 2270.98   265.1 2251.43   290.7 2249.32
   307.8 2249.17   320.6 2247.78   412.7 2227.67   418.7 2227.23   425.1 2227.74
   444.5  2231.6   457.3 2231.96   471.7 2233.62  484.68 2233.51     509 2234.63
   545.3 2238.43   573.8 2239.78   606.3 2247.67   659.3 2253.81     704 2261.68
   768.7 2264.83   785.8 2266.31   826.2 2272.14   833.7 2274.39   846.1 2279.92
#Mann= 4 ,-1 , 0
       0      .1       0   412.7    .045       0   425.1      .1       0
  484.68     .05       0
#XS Ineff= 2 , 0
          399.25 2235.42  452.53         2235.38
Permanent Ineff=
       F       F
Bank Sta=412.7,425.1
XS Rating Curve= 0 ,0
Exp/Cntr=0.5,0.3

Type RM Length L Ch R = 1 ,6757    ,49.3,55.3,62.8
XS GIS Cut Line= 3
2414831.90747146576473.0771526412415010.59749342576130.797673942
2414937.61142811575660.163390729
#Sta/Elev= 30
       0 2327.84    72.6 2301.62    81.8 2296.99    90.8 2296.29     145 2278.93
     212 2260.44   284.8 2243.48   316.4 2237.36   348.9 2232.33   375.1 2226.04
   388.4 2224.36   408.6 2227.85   413.7 2226.88   424.8 2221.34   428.8 2221.03
   434.52221.454   441.7 2224.11   453.1 2226.76  461.83 2226.88   493.6 2231.53
   546.8 2236.55   602.9 2240.37   651.9 2247.86     722 2255.11   756.7  2257.7
   772.9 2256.53     789 2259.72   825.5 2262.97   837.6 2265.89   862.4 2276.38
#Mann= 4 ,-1 , 0
       0      .1       0   424.8    .045       0   434.5      .1       0
  461.83     .05       0
#XS Ineff= 2 , 0
          407.62 2227.79  458.32         2229.86
Permanent Ineff=
       F       F
Bank Sta=424.8,434.5
XS Rating Curve= 0 ,0
Exp/Cntr(USF)=0,0
Exp/Cntr=0.3,0.1

Type RM Length L Ch R = 1 ,6702    ,129.7,126.4,127.2
XS GIS Cut Line= 3
     2414852.285      576483.4582415105.21509437576006.498085933
2415015.83851902575658.802371877
#Sta/Elev= 30
       0 2328.11      35 2314.46    79.9 2299.32    91.7 2297.73   113.3 2290.19
   130.1 2285.76   202.5 2263.26   258.4 2248.44   315.7  2235.9   340.2 2231.27
     358 2226.31   366.8 2224.56   392.6 2221.57   434.9 2218.84   442.4 2218.47
     447 2218.91   465.1 2221.47   483.2 2230.48   499.22231.306   519.4 2229.93
   539.9 2229.89   620.3 2234.05   636.8 2236.14   665.7 2242.12   690.5 2246.06
   731.9 2249.82   814.4 2254.26   843.6 2257.81   872.2 2265.88   898.9 2274.84
#Mann= 4 ,-1 , 0
       0      .1       0   434.9    .045       0     447      .1       0
   499.2     .05       0
#XS Ineff= 2 , 0
          397.46 2224.93
Permanent Ineff=
       F       F
Bank Sta=434.9,447
XS Rating Curve= 0 ,0
Exp/Cntr=0.3,0.1

Type RM Length L Ch R = 1 ,6576    ,185.6,181.3,178.9
XS GIS Cut Line= 3
2415013.97794181576539.8695820592415193.30172491  576037.2584966
2415126.19514472575721.766188363
#Sta/Elev= 30
       0 2349.19    57.7 2334.52    71.5 2328.18    84.2 2327.94   109.7 2319.88
   152.2  2310.5   203.1 2292.17   258.8 2264.29   292.3 2245.64   326.3 2235.77
   347.5 2226.48     356 2221.89   369.92210.803     373 2209.86   380.8 2210.97
   385.7 2213.37   396.5 2213.22     409 2215.19   440.9 2216.53   457.9 2222.07
   468.5 2223.79  544.992222.621   562.9 2221.59   587.5 2225.07   640.6 2228.07
   652.9 2229.55   689.7 2237.34   719.6 2242.35   783.7 2250.53   856.2 2256.49
#Mann= 4 ,-1 , 0
       0      .1       0   369.9    .045       0   380.8      .1       0
  544.99     .05       0
#XS Ineff= 2 , 0
                          410.88         2215.72
Permanent Ineff=
       F       F
Bank Sta=369.9,380.8
XS Rating Curve= 0 ,0
Exp/Cntr=0.3,0.1

Type RM Length L Ch R = 1 ,6394    ,143.3,151.9,157.7
XS GIS Cut Line= 4
2415150.00297091576559.7907873932415318.38759903 576230.82002182
2415320.53796904 576097.381117452415245.62617139575747.329195636
#Sta/Elev= 30
       0 2338.31    35.1 2328.19   108.9 2301.44   182.9 2278.98     201 2268.23
   241.8 2248.95   273.2 2237.35   358.6 2213.01   367.5 2208.87   375.8 2202.79
   379.8 2201.05   387.8 2200.27   395.8 2202.34   411.8  2203.4   415.8 2202.94
   426.92197.982   431.8  2197.4     438 2197.87   443.8 2200.43   451.8 2206.64
   465.2 2211.82   475.8  2214.1  495.66 2214.58   573.8 2215.36   585.6 2216.79
   654.6 2219.51   745.1  2232.7   792.8 2237.79   847.4 2248.63     861 2250.34
#Mann= 4 ,-1 , 0
       0      .1       0   426.9    .045       0     438      .1       0
  495.66     .05       0
Bank Sta=426.9,438
XS Rating Curve= 0 ,0
Exp/Cntr=0.3,0.1