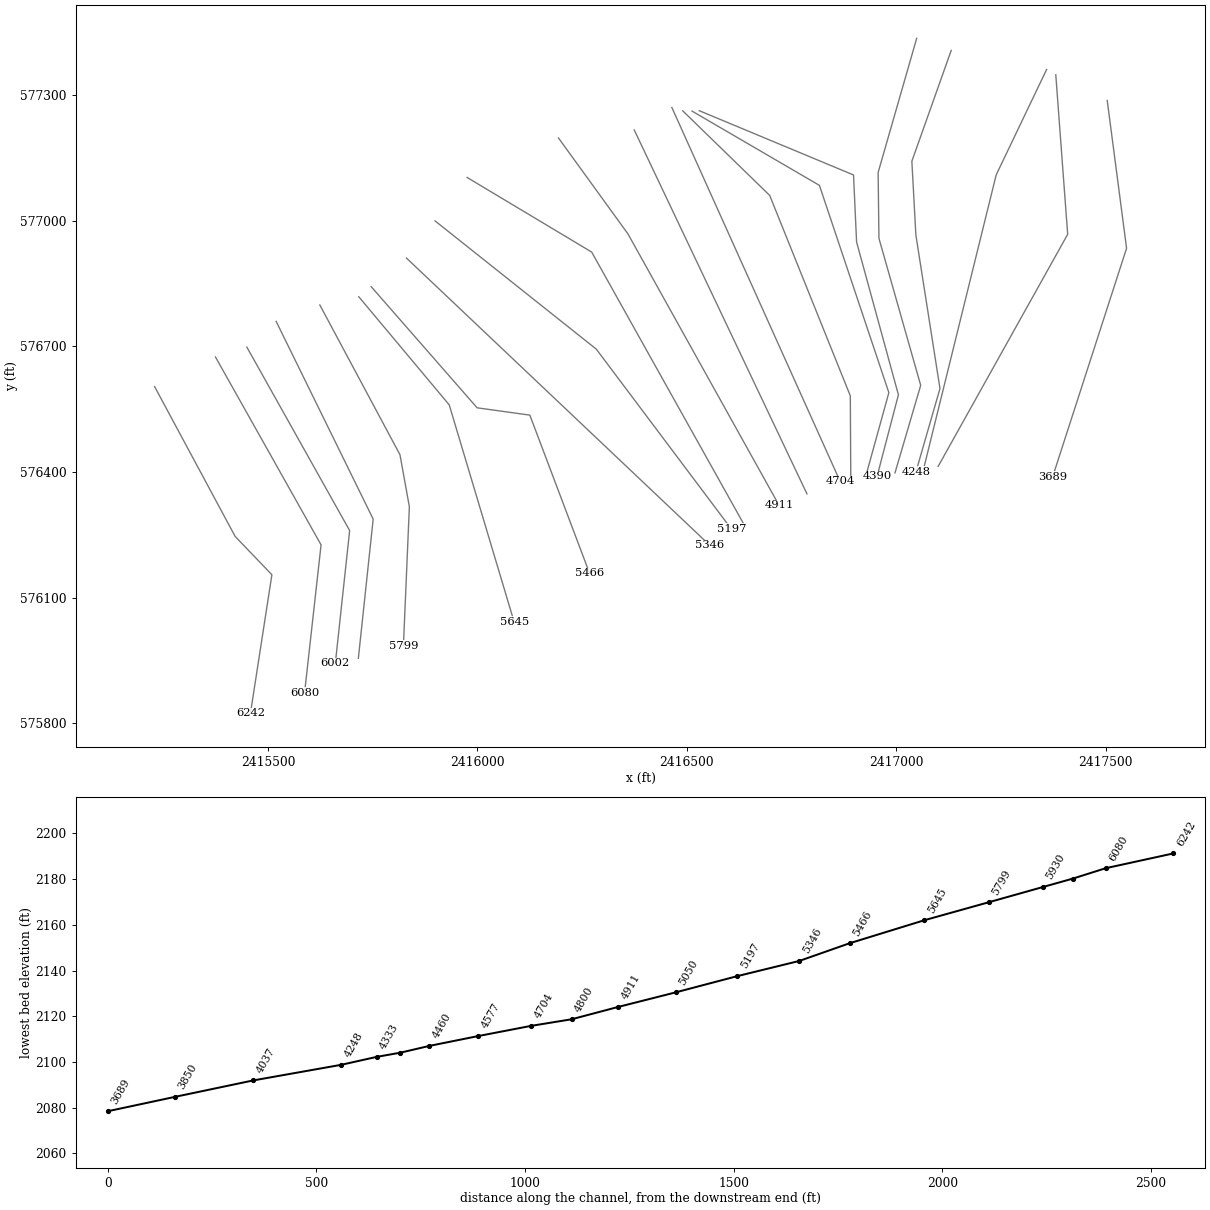
HEC-RAS study MOYERRN.prj: MOYERRN

--- MOYERRN.g01 (geometry) --- (continued)

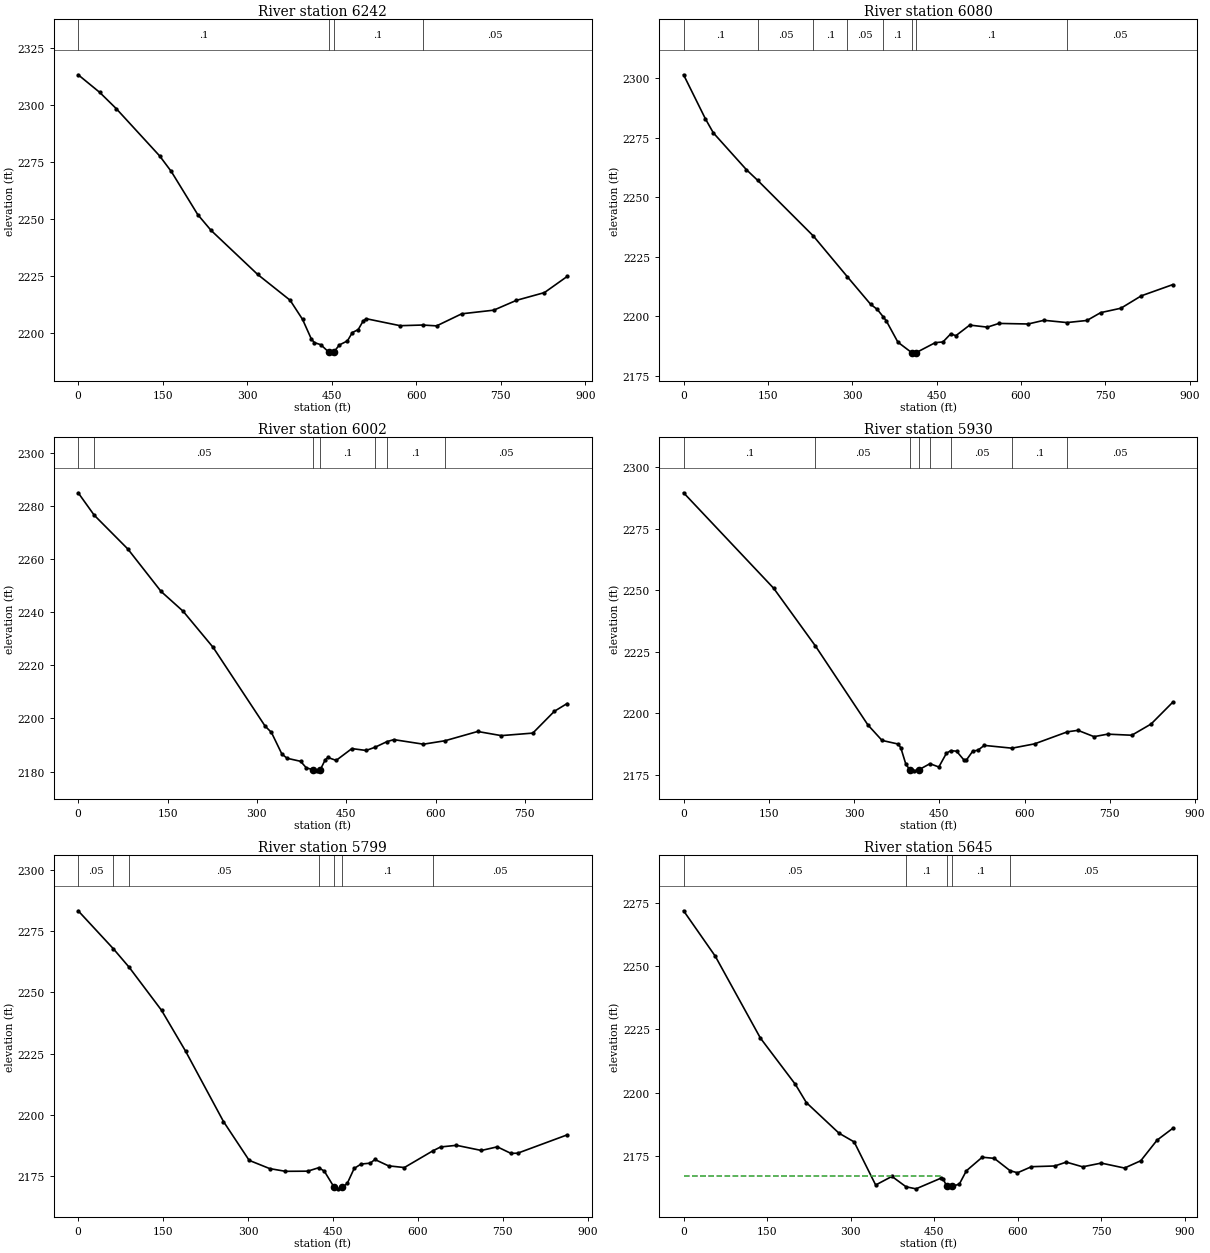
Type RM Length L Ch R = 1 ,6242    ,164.6,162.7,160.1
XS GIS Cut Line= 4
2415229.27778497 576603.868198062415421.53238885576246.219811637
 2415509.2950345 576154.707337332415458.08690302575823.645765573
#Sta/Elev= 30
       0 2313.34      38 2305.66    67.4 2298.52   144.6 2277.71   165.2  2270.9
   212.2 2251.95   235.8 2245.03   318.5 2225.68   376.1 2214.35   398.2 2205.95
   413.9 2197.28   419.4 2195.72   430.5 2194.83     4452191.517     452 2191.25
   453.52191.529   463.5  2194.7   477.8 2196.48   486.6 2200.14     497 2201.47
   506.1 2205.36   511.7 2206.21   571.4 2203.17  611.22 2203.46   636.2 2203.09
   680.7 2208.39   737.4 2209.98   777.8  2214.3   827.5  2217.7   867.8 2224.78
#Mann= 4 ,-1 , 0
       0      .1       0     445    .045       0   453.5      .1       0
  611.22     .05       0
Bank Sta=445,453.5
XS Rating Curve= 0 ,0
Exp/Cntr=0.3,0.1

Type RM Length L Ch R = 1 ,6080    ,77.2,77.6,77.6
XS GIS Cut Line= 3
     2415374.538      576674.7352415626.74387523576226.015562059
2415587.41533309575873.384572362
#Sta/Elev= 30
       0  2301.3    38.9  2282.8      53 2276.93   111.8 2261.51  132.012257.001
  230.792233.735  291.392216.613   332.6 2205.12   344.4 2202.99  354.842199.922
   360.4 2198.22   381.2 2189.22   405.7 2184.85   410.9 2184.76   413.8 2184.87
   447.6 2189.03   461.3 2189.33   475.1 2192.71   484.3 2191.96   508.9 2196.39
   540.3 2195.53   560.8 2197.09   612.8 2196.85   640.9  2198.4  681.772197.444
   717.4 2198.33   741.8 2201.61   777.8 2203.46     814 2208.65   869.6 2213.32
#Mann= 8 ,-1 , 0
       0      .1       0  132.01     .05       0  230.79      .1       0
  291.39     .05       0  354.84      .1       0   405.7    .045       0
   413.8      .1       0  681.77     .05       0
Bank Sta=405.7,413.8
XS Rating Curve= 0 ,0
Exp/Cntr=0.3,0.1

Type RM Length L Ch R = 1 ,6002    ,73.4,72.3,71.3
XS GIS Cut Line= 3
2415449.52369675576698.2806440732415694.98555966576260.177825476
2415660.80732558575943.252382235
#Sta/Elev= 30
       0 2285.04   26.892276.607    83.4 2263.85   139.2 2247.86   176.2  2240.4
   226.7 2226.75   313.8 2197.13   324.4 2194.76     342  2186.6   350.8    2185
   373.4 2183.86   383.1 2181.37   394.9 2180.67   400.9 2180.27   406.6 2180.74
   414.6 2184.37   419.2 2185.32   433.1  2184.2   459.5 2188.65   483.4 2187.95
  498.242189.145  518.252191.259   529.9 2192.03   579.6 2190.31  615.89 2191.61
   670.7  2195.1   710.3 2193.54   763.3 2194.49   799.5 2202.72   820.9 2205.63
#Mann= 7 ,-1 , 0
       0      .1       0   26.89     .05       0   394.9    .045       0
   406.6      .1       0  498.24     .05       0  518.25      .1       0
  615.89     .05       0
Bank Sta=394.9,406.6
XS Rating Curve= 0 ,0
Exp/Cntr(USF)=0,0
Exp/Cntr=0.3,0.1

Type RM Length L Ch R = 1 ,5930    ,133.7,130.5,126.7
XS GIS Cut Line= 3
     2415519.436      576759.7752415751.18371838576287.536383394
 2415715.7763646575955.160393697
#Sta/Elev= 30
       0 2289.57   158.6 2250.74   232.12227.264   324.4 2195.19   349.2 2188.92
   377.9 2187.43   382.3 2185.87   391.2 2179.16   398.42176.948   404.6 2176.56
   413.92176.986  433.492179.467   449.1 2178.12   462.5 2183.72  470.132184.775
   480.3 2184.54   493.7 2180.86     497 2180.78   508.9 2184.58   517.9 2184.94
     529  2186.9  577.82 2185.77   617.5 2187.52  675.46 2192.43   693.9 2193.02
   722.1 2190.46   746.2 2191.47   788.6 2191.03   822.6  2195.6   860.3 2204.36
#Mann= 8 ,-1 , 0
       0      .1       0   232.1     .05       0   398.4    .045       0
   413.9     .05       0  433.49      .1       0  470.13     .05       0
  577.82      .1       0  675.46     .05       0
Bank Sta=398.4,413.9
XS Rating Curve= 0 ,0
Exp/Cntr=0.3,0.1

Type RM Length L Ch R = 1 ,5799    ,152.6,154,155.3
XS GIS Cut Line= 4
2415623.77662342576798.852479686  2415815.155706576441.321174997
 2415837.5959607576317.0366874522415823.38840935575985.233653124
#Sta/Elev= 30
       0 2283.19   62.31 2267.67    90.22260.133   147.3 2242.62   189.7    2226
   256.7  2197.3   302.1 2181.47   338.4 2178.11   366.3    2177   405.5 2177.06
  425.052178.467   434.8 2177.09   451.72170.702   459.2 2169.86   466.92170.565
   475.4 2172.05   487.6 2178.17   499.8 2179.96   516.1 2180.33   524.2 2181.82
   548.3 2179.23   576.3 2178.54  626.552185.335   640.4 2186.93   668.4  2187.6
   712.4  2185.5   740.5 2186.98   764.5 2184.32   776.5 2184.39   863.9 2191.85
#Mann= 7 ,-1 , 0
       0     .05       0   62.31      .1       0    90.2     .05       0
  425.05      .1       0   451.7    .045       0   466.9      .1       0
  626.55     .05       0
Bank Sta=451.7,466.9
XS Rating Curve= 0 ,0
Exp/Cntr=0.3,0.1

Type RM Length L Ch R = 1 ,5645    ,167.3,179.1,190.8
XS GIS Cut Line= 3
     2415716.787       576818.542415932.77766405576560.400528174
     2416087.786      576041.978
#Sta/Elev= 30
       0 2271.75    56.9 2253.82   137.9 2221.51   200.8  2203.2   220.4 2196.04
     279 2183.97   306.2 2180.53   344.8 2163.52     374 2166.92  399.33 2162.82
   417.2 2162.01   461.7 2166.19   465.9 2165.93   472.42163.026   482.6 2162.97
   495.1 2163.92   507.6 2169.13   536.1 2174.49   557.7 2174.04  586.132169.162
   599.4 2168.35   624.5 2170.75   666.2 2171.03     687 2172.56   716.3  2170.7
   749.7 2172.17   791.5 2170.22   820.7  2173.1   849.9 2181.22   877.7 2185.83
#Mann= 5 ,-1 , 0
       0     .05       0  399.33      .1       0   472.4    .045       0
   482.6      .1       0  586.13     .05       0
#XS Ineff= 2 , 0
          461.96 2167.16
Permanent Ineff=
       F       F
Bank Sta=472.4,482.6
XS Rating Curve= 0 ,0
Exp/Cntr=0.3,0.1

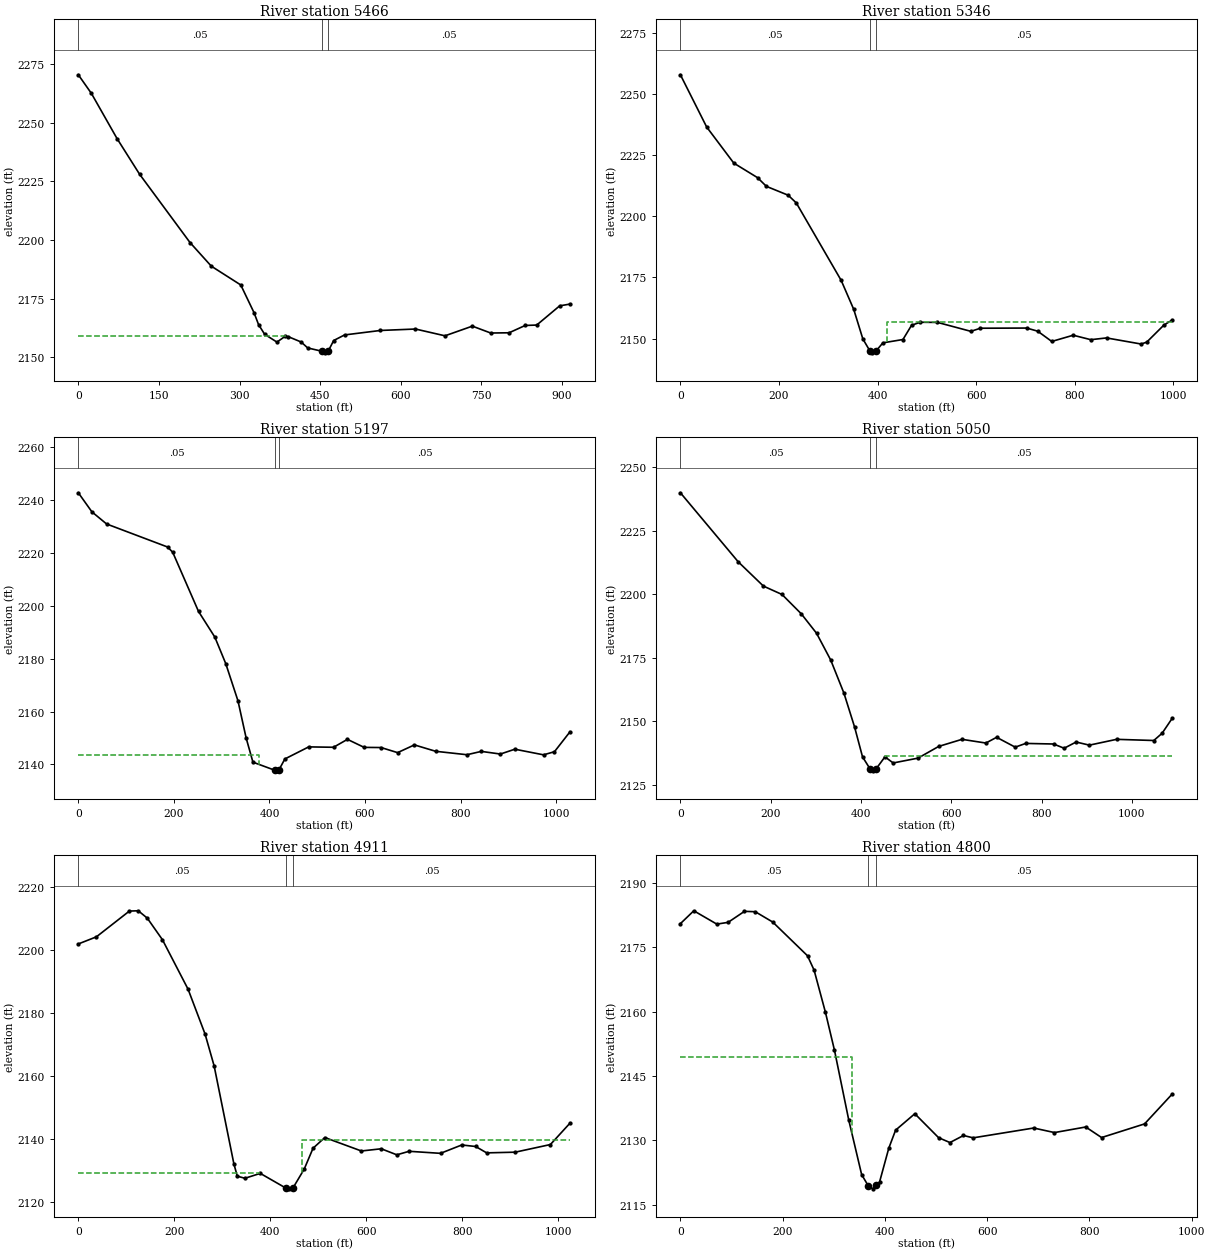
Type RM Length L Ch R = 1 ,5466    ,125.9,120.3,112.7
XS GIS Cut Line= 4
     2415746.285      576842.8052415999.39315102576553.322439249
2416125.29153372576535.8771199962416267.78474473576158.586951319
#Sta/Elev= 30
       0 2270.34    24.3 2262.43    72.1 2243.16   113.9 2228.03   207.8 2198.92
   247.5 2188.84   302.3 2180.84   326.9 2169.08   335.4 2163.96   346.7 2159.85
   369.6 2156.51   384.5 2158.91   390.3 2158.86   414.7 2156.55   426.8 2154.03
   453.42152.616   459.1 2151.94   464.9 2152.62   475.2 2157.19   495.4 2159.56
   562.2 2161.47   627.4 2162.08   682.3 2159.19   733.2 2163.31   767.4 2160.38
   801.6 2160.48   831.6  2163.6     853 2163.77   895.7 2171.95   914.9  2172.7
#Mann= 3 ,-1 , 0
       0     .05       0   453.4    .045       0   464.9     .05       0
#XS Ineff= 2 , 0
          387.96 2159.23
Permanent Ineff=
       F       F
Bank Sta=453.4,464.9
XS Rating Curve= 0 ,0
Exp/Cntr=0.3,0.1

Type RM Length L Ch R = 1 ,5346    ,147.8,148.6,149
XS GIS Cut Line= 2
2415830.56550172576910.9987968562416554.86970142576225.113420082
#Sta/Elev= 30
       0 2257.75    53.3 2236.42   108.3 2221.69   156.5 2215.74   174.5 2212.19
   218.6 2208.58   235.1 2205.43   326.2 2173.79   351.7 2161.94   370.1 2149.92
   384.82144.874   388.5 2144.22   396.42144.861   410.8  2148.3   451.5 2149.66
     469 2155.48   486.4  2156.7   521.5 2156.65   589.3    2153   608.6 2154.27
   702.5 2154.34   724.9 2153.06   753.4 2148.87   796.9 2151.41   832.6 2149.59
   864.5 2150.31   934.6 2147.82     946 2148.58   980.9 2155.55   997.5 2157.59
#Mann= 3 ,-1 , 0
       0     .05       0   384.8    .045       0   396.4     .05       0
#XS Ineff= 2 , 0
                          419.49         2156.97
Permanent Ineff=
       F       F
Bank Sta=384.8,396.4
XS Rating Curve= 0 ,0
Exp/Cntr=0.3,0.1

Type RM Length L Ch R = 1 ,5197    ,151.4,147.4,142.9
XS GIS Cut Line= 3
     2415898.948      576999.654 2416283.9751146576693.432796856
2416606.31437677576264.120302029
#Sta/Elev= 30
       0 2242.84    28.5 2235.61    59.2 2231.03   186.9  2222.3   197.5 2220.33
   251.5 2197.93   285.7 2188.19   308.5 2178.17   334.1 2164.06   351.2 2149.98
   365.4 2140.85   411.8 2137.75   416.6 2137.57   419.5 2137.82   432.2 2142.07
   482.1 2146.64     534 2146.49   563.1 2149.49   598.1 2146.45   633.5 2146.39
   668.1 2144.46   703.2 2147.39   747.7 2144.97   813.2 2143.67   843.2 2144.93
   883.2 2143.93   913.4 2145.76   973.4 2143.63   996.3 2144.81  1028.8 2152.35
#Mann= 3 ,-1 , 0
       0     .05       0   411.8    .045       0   419.5     .05       0
#XS Ineff= 2 , 0
          378.87 2143.71
Permanent Ineff=
       F       F
Bank Sta=411.8,419.5
XS Rating Curve= 0 ,0
Exp/Cntr=0.3,0.1

Type RM Length L Ch R = 1 ,5050    ,136.6,139,139.4
XS GIS Cut Line= 3
2415975.43394787577103.445416633 2416272.9752612576925.225128818
2416635.21240629576277.288508621
#Sta/Elev= 30
       0 2240.01     128 2212.83   183.9 2203.25   225.1 2199.95   267.9 2192.31
   301.6 2184.68     333 2174.12   362.3 2161.07   385.8 2147.78   403.4 2136.01
   420.8 2131.05   425.6 2130.48   432.8 2131.08   453.1 2135.99   471.4 2133.58
   526.4 2135.49   572.2  2140.1   623.8 2142.89   676.7 2141.43   700.5 2143.69
   741.7 2139.81   764.9 2141.28   826.6 2141.05   850.1 2139.38   876.6 2141.83
     906  2140.6   966.3 2142.89  1048.7 2142.43  1067.1 2145.28  1089.2  2151.1
#Mann= 3 ,-1 , 0
       0     .05       0   420.8    .045       0   432.8     .05       0
#XS Ineff= 2 , 0
                          453.47         2136.18
Permanent Ineff=
       F       F
Bank Sta=420.8,432.8
XS Rating Curve= 0 ,0
Exp/Cntr=0.3,0.1

Type RM Length L Ch R = 1 ,4911    ,111.6,110.7,109.7
XS GIS Cut Line= 3
2416193.73195132577197.6141805282416359.68044615 576968.46896359
2416720.18866846576320.903977384
#Sta/Elev= 30
       0    2202    37.7 2204.27   106.4 2212.47   124.9 2212.56   143.7 2210.21
   175.2 2203.35   228.6  2187.6     264 2173.33   282.9 2163.18   324.1 2131.96
   331.1 2128.09     347 2127.41     379 2128.97   431.82124.335   438.5 2124.05
   447.42124.399   470.6 2130.36   488.9 2136.97   513.4 2140.38   589.6  2136.1
     631  2136.8   663.4 2134.88     689    2136   754.4 2135.35   798.6 2138.01
   827.6 2137.53   850.5  2135.5     910 2135.72   983.3 2138.15  1024.1 2144.96
#Mann= 3 ,-1 , 0
       0     .05       0   431.8    .045       0   447.4     .05       0
#XS Ineff= 2 , 0
           378.8  2129.2  465.78         2139.51
Permanent Ineff=
       F       F
Bank Sta=431.8,447.4
XS Rating Curve= 0 ,0
Exp/Cntr=0.3,0.1

Type RM Length L Ch R = 1 ,4800    ,96.8,96.6,96.4
XS GIS Cut Line= 2
  2416374.627697577216.7566428132416786.99135167576347.916012289
#Sta/Elev= 30
       0 2180.53    26.2 2183.53    71.2 2180.42    93.3 2180.83   125.3  2183.4
   146.4 2183.31   180.6  2180.9   248.6 2173.04   261.5 2169.69   283.7 2159.85
   301.4 2150.99   329.4 2134.68   354.5 2122.02   367.52119.388   376.6  2118.7
   382.52119.525   389.5 2120.28   407.6 2128.18   420.9 2132.38   458.5 2136.21
     505 2130.63   527.2 2129.49   553.7 2131.14   572.6 2130.59     691 2132.88
   731.7 2131.82   792.8 2133.12   823.8 2130.66   907.9 2133.84   961.7 2140.77
#Mann= 3 ,-1 , 0
       0     .05       0   367.5    .045       0   382.5     .05       0
#XS Ineff= 2 , 0
          335.96 2149.52
Permanent Ineff=
       F       F
Bank Sta=367.5,382.5
XS Rating Curve= 0 ,0
Exp/Cntr(USF)=0,0
Exp/Cntr=0.3,0.1

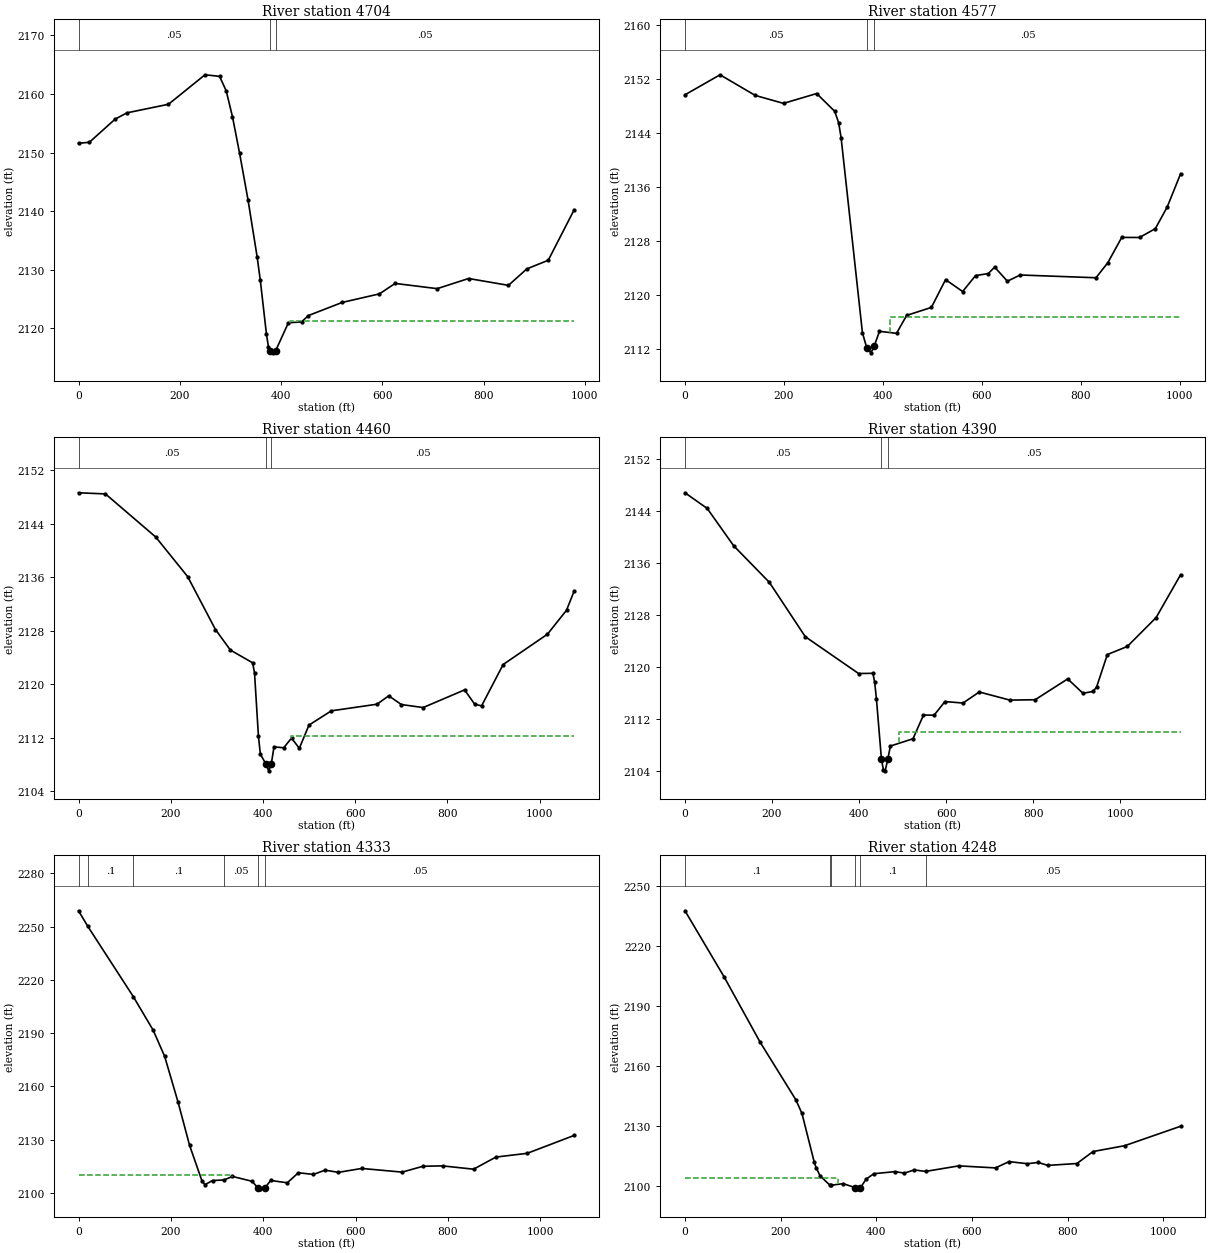
Type RM Length L Ch R = 1 ,4704    ,127.1,126.6,125.6
XS GIS Cut Line= 2
2416464.40040974577270.522295132 2416866.1584358576377.838390569
#Sta/Elev= 30
       0 2151.57    21.5 2151.75    72.4  2155.7    95.9 2156.77   177.7 2158.23
   249.8 2163.26   278.6 2162.99   291.7 2160.52   304.1 2156.09   318.1 2149.88
   334.9 2141.86   352.8 2132.18   359.1 2128.17   371.2 2118.99   375.1 2116.87
   378.5  2116.2   383.8 2115.83   389.3 2116.18   414.5 2120.96   440.5 2121.11
     454 2122.19   520.9 2124.43   594.4 2125.89   625.3 2127.67   708.4 2126.78
   770.4 2128.51   849.1 2127.34   885.4 2130.15   927.7 2131.62   978.9 2140.23
#Mann= 3 ,-1 , 0
       0     .05       0   378.5    .045       0   389.3     .05       0
#XS Ineff= 2 , 0
                          417.83         2121.23
Permanent Ineff=
       F       F
Bank Sta=378.5,389.3
XS Rating Curve= 0 ,0
Exp/Cntr=0.3,0.1

Type RM Length L Ch R = 1 ,4577    ,117.9,117.4,116.6
XS GIS Cut Line= 4
2416490.39394442577262.5084166332416698.05826562 577060.52270142
2416890.56175795 576581.908411682416891.69385243576385.442275965
#Sta/Elev= 30
       0 2149.63    70.9  2152.6     142 2149.54   199.2 2148.36   266.2 2149.82
   302.7 2147.18   310.6 2145.51   315.6 2143.29   358.7 2114.38   367.3 2112.14
     376 2111.38   382.5 2112.38   393.2 2114.57   427.7 2114.27   448.1 2116.93
   498.1 2118.11   526.8 2122.23   561.3 2120.47   587.4 2122.83   613.1 2123.13
     626 2124.09   651.8    2122   677.7 2122.92   830.9 2122.51   854.9 2124.75
   882.9 2128.49   918.9 2128.48   950.9 2129.79   974.9 2133.01    1002 2137.94
#Mann= 3 ,-1 , 0
       0     .05       0   367.3    .045       0   382.5     .05       0
#XS Ineff= 2 , 0
                          413.76         2116.69
Permanent Ineff=
       F       F
Bank Sta=367.3,382.5
XS Rating Curve= 0 ,0
Exp/Cntr=0.3,0.1

Type RM Length L Ch R = 1 ,4460    ,72.7,69.3,65.8
XS GIS Cut Line= 4
2416512.56780375577261.8892725162416816.79453124577084.514232657
2416982.62434132576589.5802936272416929.16291146576396.051334991
#Sta/Elev= 30
       0 2148.62    58.4 2148.45   167.4 2142.01   236.8 2136.08     297 2128.18
   329.4 2125.11   377.5 2123.21   381.7 2121.71   390.2 2112.22   394.4 2109.54
     407 2108.02   412.5 2107.06   417.92108.011   423.9 2110.64     445 2110.51
   461.9 2111.95   478.9 2110.43   499.8  2113.9   548.4 2116.03   647.5 2117.02
   672.8 2118.28     700 2116.97   747.4 2116.52   837.3 2119.16   859.1 2117.02
   874.1 2116.77   920.9 2122.95  1016.9 2127.48  1058.3 2131.06  1074.9 2133.93
#Mann= 3 ,-1 , 0
       0     .05       0     407    .045       0   417.9     .05       0
#XS Ineff= 2 , 0
                          459.98          2112.2
Permanent Ineff=
       F       F
Bank Sta=407,417.9
XS Rating Curve= 0 ,0
Exp/Cntr=0.5,0.3

Type RM Length L Ch R = 1 ,4390    ,57.3,57.1,56.5
XS GIS Cut Line= 5
2416529.98330643577262.787934496 2416898.2336399577109.350295552
2416905.54370439576949.2600628132417005.43394343576584.354903868
2416954.46953575576389.670866553
#Sta/Elev= 30
       0 2146.84    51.1 2144.43   111.8  2138.7   193.9 2133.07   276.4 2124.72
   398.8 2119.06   431.8 2119.09   435.8 2117.75   439.9 2115.14   451.3 2105.96
   455.9 2104.23   459.9  2104.1   465.92105.849   471.9 2107.91   523.9 2109.03
     548 2112.68   572.3 2112.65   597.3 2114.75   638.8 2114.52   676.1 2116.22
   746.6 2114.97   804.6 2115.03   879.3 2118.23   914.4 2116.02   937.1  2116.3
   945.6 2116.96   970.4 2121.97  1016.3 2123.22  1082.5 2127.66  1138.8 2134.25
#Mann= 3 ,-1 , 0
       0     .05       0   451.3    .045       0   465.9     .05       0
#XS Ineff= 2 , 0
          440.61 2108.65  492.65         2110.09
Permanent Ineff=
       F       F
Bank Sta=451.3,465.9
XS Rating Curve= 0 ,0
Exp/Cntr(USF)=0,0
Exp/Cntr=0.5,0.3

Type RM Length L Ch R = 1 ,4333    ,84.4,84.8,85.7
XS GIS Cut Line= 5
2417049.05721741577435.6305573692416956.99463404577115.329486072
2416958.91260453576958.0559061542417058.64706984576607.067307068
2416997.27201427576398.008524006
#Sta/Elev= 30
       0 2258.92   20.242250.086  118.542210.593   161.5 2191.71   186.4    2177
   215.6 2151.08   240.5 2126.76   267.6  2106.5   273.8 2104.58   290.2 2106.93
  315.152107.253   333.3 2109.23   376.1 2106.49   388.1 2102.83   392.1 2102.25
   404.1 2102.94   416.1 2106.97   452.1 2105.66   476.1 2111.31   508.8 2110.38
   533.8 2112.77   562.9 2111.55   613.4 2113.74   700.9 2111.67   745.8 2114.96
   788.3 2115.19   855.5 2113.32   903.9 2120.16   971.5 2122.25  1073.3 2132.35
#Mann= 6 ,-1 , 0
       0     .12       0   20.24      .1       0  118.54      .1       0
  315.15     .05       0   388.1    .045       0   404.1     .05       0
#XS Ineff= 2 , 0
          331.45 2109.92
Permanent Ineff=
       F       F
Bank Sta=388.1,404.1
XS Rating Curve= 0 ,0
Exp/Cntr(USF)=0,0
Exp/Cntr=0.5,0.3

Type RM Length L Ch R = 1 ,4248    ,214.1,211.4,208.1
XS GIS Cut Line= 5
2417131.52994834577406.8610000672417037.54939449577142.181072887
2417047.13924692576965.7277881012417104.67836153576599.395425121
2417047.13924692576399.926494493
#Sta/Elev= 30
       0 2237.47    82.1 2204.37   157.2 2171.88   231.8 2143.18   244.5 2136.39
   270.1 2112.17   274.2 2109.28   282.6  2105.2  302.26 2100.78  305.67 2100.59
   330.6 2101.38   355.1 2099.45   362.7 2098.79   366.7 2099.34   378.7 2103.64
   394.7 2106.33   438.8 2107.38   458.8 2106.63   479.1 2108.22  502.832107.481
   572.2 2110.24   649.1 2109.23   677.4 2112.37   715.8 2111.32   738.2 2111.96
   758.4 2110.48   819.2 2111.42     853  2117.4   918.8 2120.29    1036 2130.01
#Mann= 6 ,-1 , 0
       0      .1       0  302.26     .05       0  305.67      .1       0
   355.1    .045       0   366.7      .1       0  502.83     .05       0
#XS Ineff= 2 , 0
          318.88 2104.28
Permanent Ineff=
       F       F
Bank Sta=355.1,366.7
XS Rating Curve= 0 ,0
Exp/Cntr(USF)=0,0
Exp/Cntr=0.3,0.1

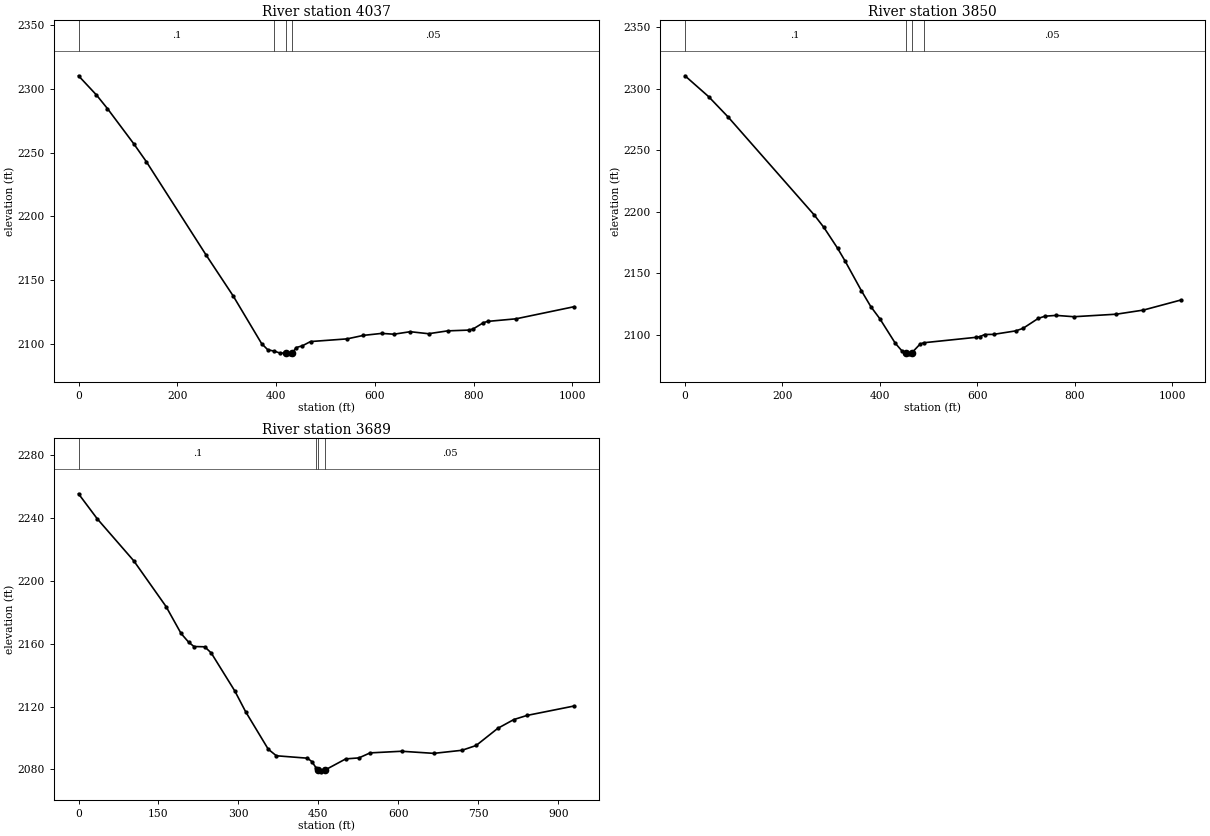
Type RM Length L Ch R = 1 ,4037    ,189.8,186.7,183.8
XS GIS Cut Line= 3
2417359.34035761577361.2294982762417238.93629561577109.575574611
2417065.27691491576406.294449595
#Sta/Elev= 30
       0  2310.4    36.3 2295.33    58.5 2284.66   111.7 2257.07   137.2 2242.99
     258 2169.76   313.1 2137.44   370.7 2099.97   383.1 2095.15  396.582094.018
   407.8 2092.57   420.2  2092.5   428.4 2091.94   432.5 2092.51   440.8  2096.9
   453.1 2098.24   469.7 2101.59   543.8  2103.7   576.7 2106.44   613.8    2108
   638.5 2107.36   671.5 2109.33   708.6 2107.75   747.2 2109.98     791 2110.61
   799.2 2111.56   819.8 2116.44     828 2117.42   885.7 2119.46  1003.4 2128.98
#Mann= 4 ,-1 , 0
       0      .1       0  396.58     .05       0   420.2    .045       0
   432.5     .05       0
Bank Sta=420.2,432.5
XS Rating Curve= 0 ,0
Exp/Cntr=0.3,0.1

Type RM Length L Ch R = 1 ,3850    ,158.9,161.4,163.5
XS GIS Cut Line= 3
2417381.22615791 577348.678524342417409.63566893576967.645758588
2417100.30565044576413.401144242
#Sta/Elev= 30
       0 2310.42    48.4 2293.54    88.5 2276.98   265.1  2197.5     285 2187.34
   313.1 2170.45   328.6 2159.99   362.1 2135.88   381.2 2123.12   399.6 2113.35
   431.5 2093.35   445.2  2087.1   452.62085.604     459 2084.78   465.82085.828
   481.9 2092.52  489.422093.768   596.5 2098.16   605.6 2098.81   614.7 2100.47
     633 2100.57   678.8 2103.43   693.5 2105.47   724.6 2113.51   738.4 2115.32
   761.3 2115.98   797.9  2114.9     885 2116.96   940.4 2120.29  1016.8  2128.4
#Mann= 4 ,-1 , 0
       0      .1       0   452.6    .045       0   465.8      .1       0
  489.42     .05       0
Bank Sta=452.6,465.8
XS Rating Curve= 0 ,0
Exp/Cntr=0.3,0.1

Type RM Length L Ch R = 1 ,3689    ,193.5,195.9,198.2
XS GIS Cut Line= 3
2417504.06045752577287.263879648 2417550.2932531576934.337446022
2417373.66743363576388.320963715
#Sta/Elev= 30
       0 2255.45    35.1 2239.54   103.7 2212.77   164.2  2183.7   192.4 2166.54
   206.7 2160.96   216.6 2158.24   236.8 2158.06   248.9 2154.17   293.3 2129.89
   313.4 2116.81   355.9  2092.9   371.1 2088.71   429.3 2087.17   437.8 2084.99
   446.42080.635   448.8 2079.62   454.6 2078.48   462.92079.715   501.3 2086.72
     526 2087.35     547 2090.54   606.1 2091.58   666.5 2090.24   719.4  2092.2
   745.9 2095.25   786.6 2106.19   816.7 2111.77   841.3 2114.38   929.8 2120.39
#Mann= 4 ,-1 , 0
       0      .1       0   446.4     .05       0   448.8    .045       0
   462.9     .05       0
Bank Sta=448.8,462.9
XS Rating Curve= 0 ,0
Exp/Cntr=0.3,0.1