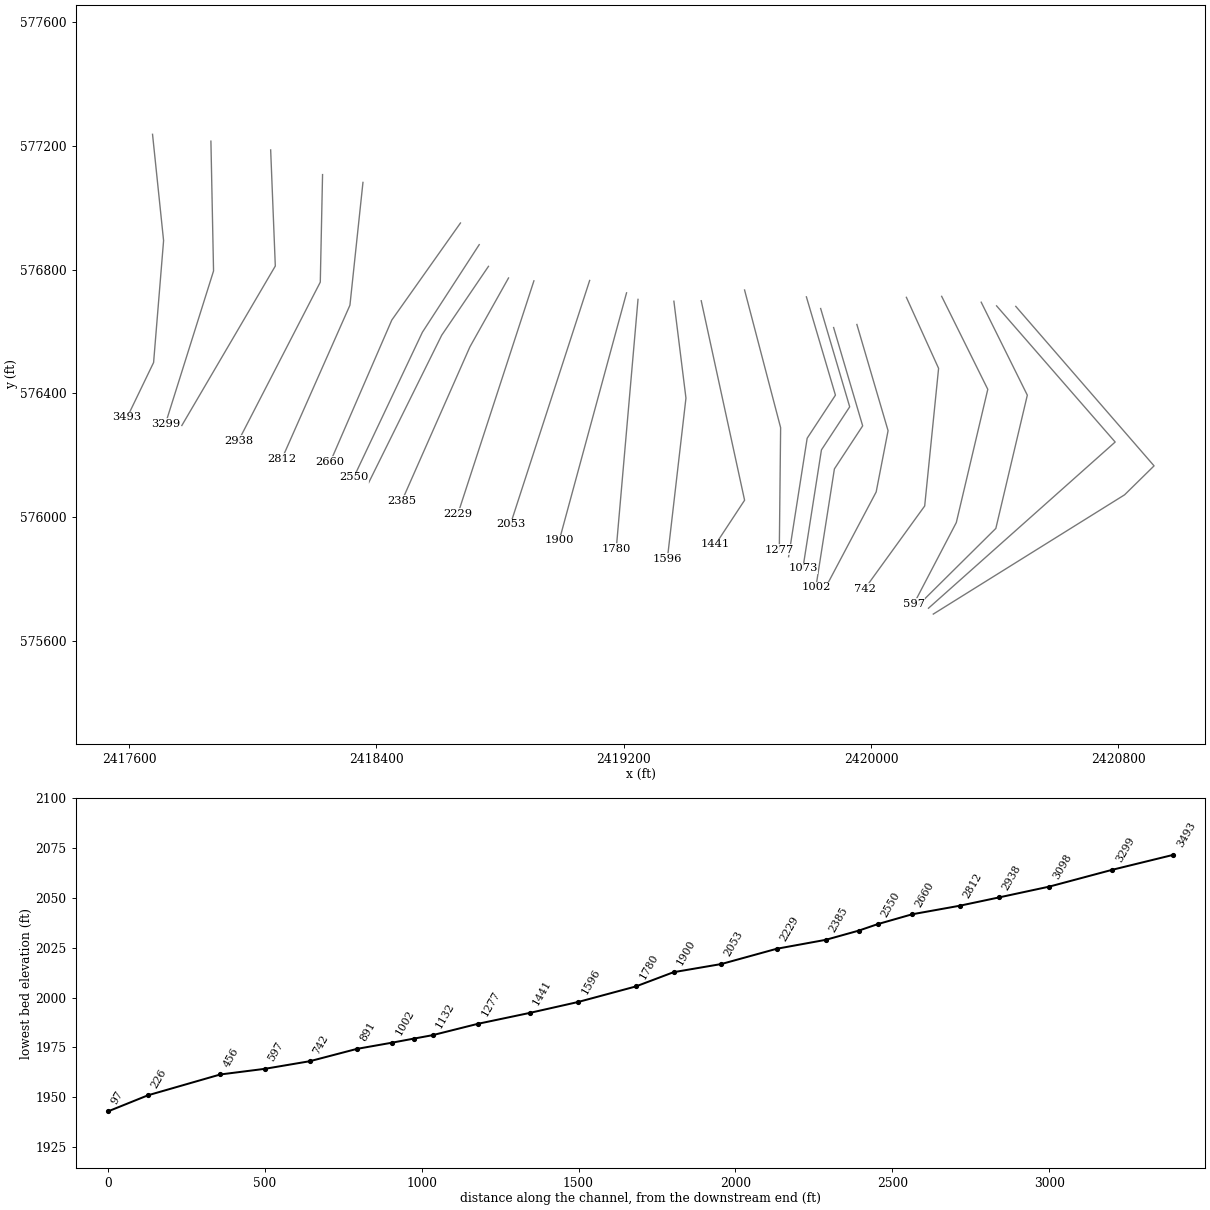
HEC-RAS study MOYERRN.prj: MOYERRN

--- MOYERRN.g01 (geometry) --- (continued)

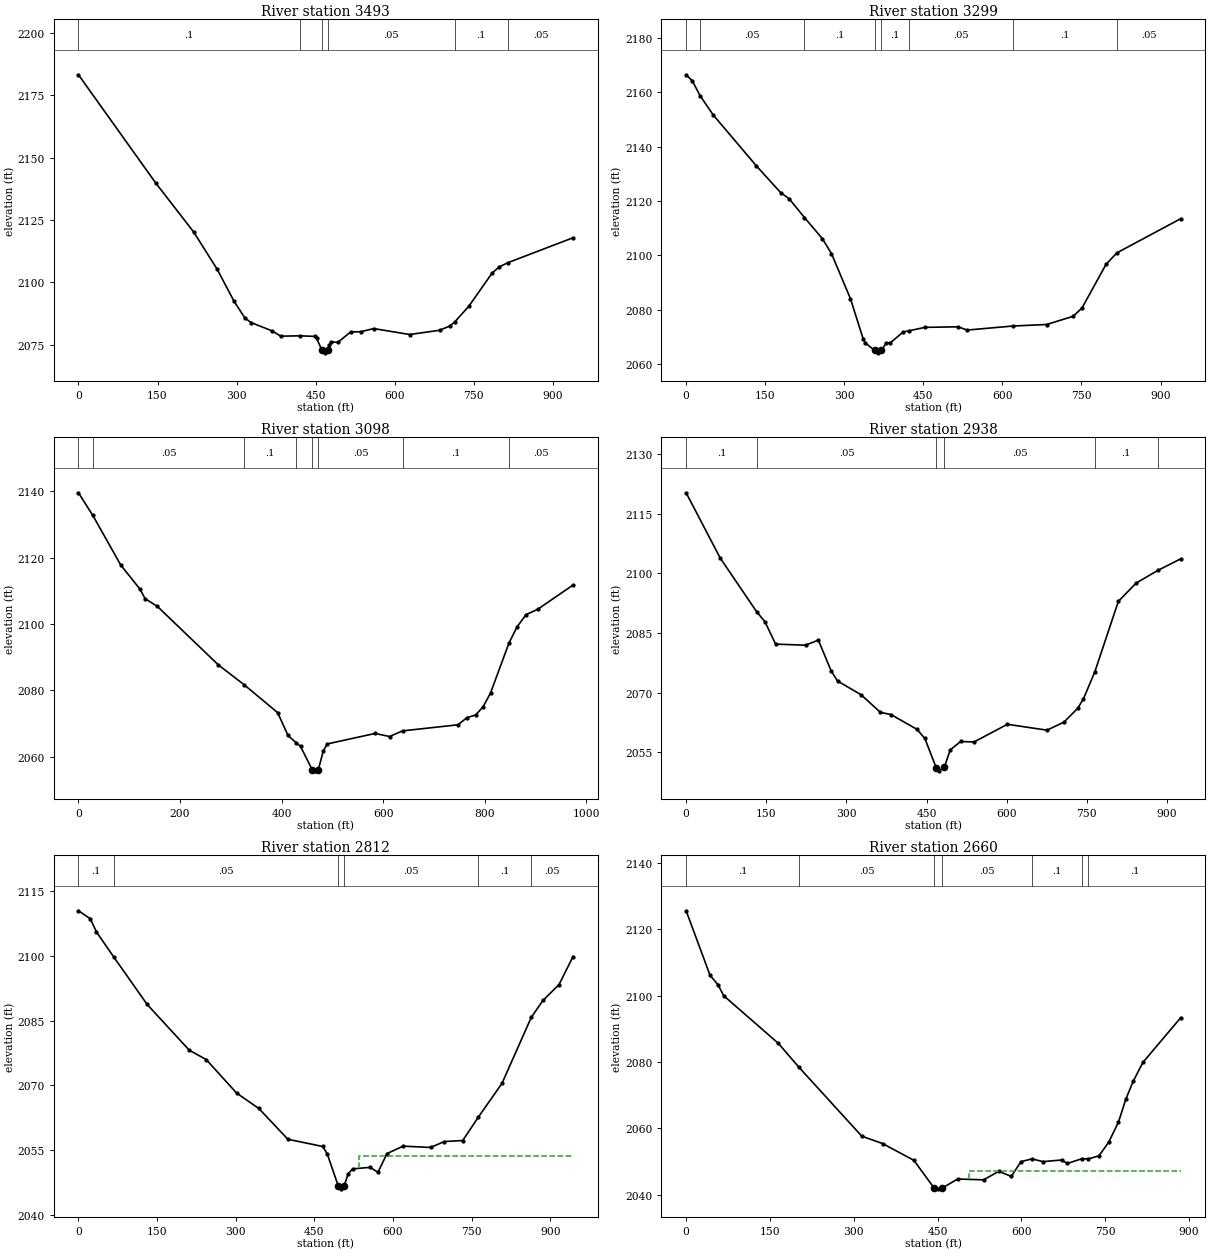
Type RM Length L Ch R = 1 ,3493    ,194.3,194.3,195.7
XS GIS Cut Line= 4
2417676.22323496577238.2534699122417711.97003629576894.326759296
2417679.64329191576500.0871754712417594.08338585576322.591084066
#Sta/Elev= 30
       0 2183.27   146.6 2139.83   218.9 2120.08   263.2 2105.21   295.3 2092.33
   315.7 2085.68   327.5 2083.81   367.7 2080.45   383.7 2078.35  420.592078.493
   447.9 2078.26     452 2077.48   461.4 2072.94     468 2071.66   472.6 2072.97
     476 2074.88     480  2076.1   492.1 2075.82   516.2 2080.01   536.2 2080.16
   560.3  2081.4   628.5 2079.01   685.6 2080.74   704.8 2082.46  713.942084.054
   740.9 2090.41   784.9 2103.69   798.6 2106.17  814.712107.835   938.4 2117.85
#Mann= 6 ,-1 , 0
       0      .1       0  420.59     .05       0   461.4    .045       0
   472.6     .05       0  713.94      .1       0  814.71     .05       0
Bank Sta=461.4,472.6
XS Rating Curve= 0 ,0
Exp/Cntr=0.3,0.1

Type RM Length L Ch R = 1 ,3299    ,208.7,201.1,196
XS GIS Cut Line= 3
2417865.04710563577216.1294905452417873.57141891576796.307061766
2417718.00270164576301.896891834
#Sta/Elev= 30
       0 2166.42    11.7  2164.2   26.392158.755    51.7 2151.57     133 2132.98
   179.3  2123.1   195.7 2120.79  224.452113.928   258.5 2106.15   275.7 2100.69
   311.7  2084.1   335.7 2069.42   339.7 2067.84   357.52065.072   363.7 2064.17
   370.3 2065.06   379.7 2067.83   387.7 2067.92   411.7 2071.83   422.52072.277
   453.2 2073.54   516.1 2073.74   532.9 2072.54   619.82074.031   683.9 2074.59
   734.2 2077.61   750.9 2080.64   796.5 2096.67  817.092100.926   938.2  2113.5
#Mann= 8 ,-1 , 0
       0      .1       0   26.39     .05       0  224.45      .1       0
   357.5    .045       0   370.3      .1       0   422.5     .05       0
   619.8      .1       0  817.09     .05       0
Bank Sta=357.5,370.3
XS Rating Curve= 0 ,0
Exp/Cntr(USF)=0,0
Exp/Cntr=0.3,0.1

Type RM Length L Ch R = 1 ,3098    ,158.8,159.7,160.2
XS GIS Cut Line= 3
2418058.31568008577187.6845606262418073.34048806576812.202897791
2417771.01486725576296.383885396
#Sta/Elev= 30
       0 2139.55   28.082132.771    83.3 2117.75   121.2 2110.48   131.3  2107.6
   155.3  2105.3   275.4 2087.66  326.272081.665   392.2 2073.26   412.5 2066.38
   428.4 2064.22   437.2 2063.09   460.5 2055.94   466.4 2055.71   472.2    2056
   482.1 2061.76   489.8 2063.82     584 2066.98   612.5 2066.06  638.11 2067.76
     747 2069.59   764.8 2071.74   782.1 2072.57   796.7 2075.03   811.3 2079.18
  847.812094.324   863.9 2099.22   881.4 2102.82   903.9 2104.39   973.7 2111.73
#Mann= 8 ,-1 , 0
       0      .1       0   28.08     .05       0  326.27      .1       0
   428.4     .05       0   460.5    .045       0   472.2     .05       0
  638.11      .1       0  847.81     .05       0
Bank Sta=460.5,472.2
XS Rating Curve= 0 ,0
Exp/Cntr=0.3,0.1

Type RM Length L Ch R = 1 ,2938    ,125.3,125.9,126.5
XS GIS Cut Line= 3
2418226.14845752 577107.934524342418218.80610653576760.078730349
2417953.97429513576246.475668582
#Sta/Elev= 30
       0 2120.32    63.7 2103.91  131.832090.399   147.5 2087.87   167.5 2082.21
   223.5 2081.94   247.5 2083.22   271.5 2075.46   283.5 2072.92   327.5 2069.46
   363.8 2065.02   383.4 2064.48   432.1 2060.75   446.9 2058.45   468.22051.066
   473.6  2050.3   483.22051.143   494.4 2055.58   513.9 2057.69     539 2057.57
   601.3 2062.02   675.5 2060.54   707.4 2062.58     733 2066.04   743.8 2068.44
  765.192075.274   809.1 2092.98   842.4 2097.58  882.832100.762   925.8 2103.69
#Mann= 6 ,-1 , 0
       0      .1       0  131.83     .05       0   468.2    .045       0
   483.2     .05       0  765.19      .1       0  882.83     .05       0
Bank Sta=468.2,483.2
XS Rating Curve= 0 ,0
Exp/Cntr=0.3,0.1

Type RM Length L Ch R = 1 ,2812    ,152.3,151.6,151.3
XS GIS Cut Line= 3
 2418356.8397469577082.7322110662418314.70463087576685.490989195
2418094.50877079576188.118921681
#Sta/Elev= 30
       0 2110.39    22.4 2108.57    34.4 2105.49   67.292099.716     131 2088.74
   211.4 2078.15   243.6    2076   301.8 2068.23   344.1 2064.68   399.5 2057.56
   466.1 2055.89   474.9 2054.09   495.5 2046.78   501.1  2046.1   506.82046.776
   514.3 2049.53     523 2050.72   556.1 2051.06   571.3 2049.94   588.6 2054.25
   619.2 2055.97   671.7 2055.67     698 2057.04     733 2057.27  762.832062.686
   807.8 2070.46  863.822085.758     886 2089.65   916.7 2093.32   943.4  2099.8
#Mann= 6 ,-1 , 0
       0      .1       0   67.29     .05       0   495.5    .045       0
   506.8     .05       0  762.83      .1       0  863.82     .05       0
#XS Ineff= 2 , 0
                          534.37         2053.69
Permanent Ineff=
       F       F
Bank Sta=495.5,506.8
XS Rating Curve= 0 ,0
Exp/Cntr=0.3,0.1

Type RM Length L Ch R = 1 ,2660    ,110.5,110.3,109.7
XS GIS Cut Line= 3
 2418672.1981385576951.3686628352418450.08746991576637.378662835
     2418251.139      576178.434
#Sta/Elev= 30
       0 2125.52    42.7 2106.14    57.4 2103.16    67.2 2099.95   164.9 2085.63
  202.012078.382   314.3 2057.66   351.4 2055.45   407.4  2050.4   443.62042.078
     450 2041.81   458.62042.093   485.8 2044.77   532.1 2044.52   559.4 2047.08
   581.7 2045.55   599.1 2049.99  618.792050.836   638.4    2050   671.9  2050.5
     682 2049.44  707.652050.856  719.582050.815   738.6 2051.76   756.1 2055.87
   773.5 2061.91   786.6 2068.79   799.7 2074.13   817.1 2079.85   884.8 2093.32
#Mann= 7 ,-1 , 0
       0      .1       0  202.01     .05       0   443.6    .045       0
   458.6     .05       0  618.79      .1       0  707.65     .05       0
  719.58      .1       0
#XS Ineff= 2 , 0
                          505.62         2047.24
Permanent Ineff=
       F       F
Bank Sta=443.6,458.6
XS Rating Curve= 0 ,0
Exp/Cntr=0.5,0.3

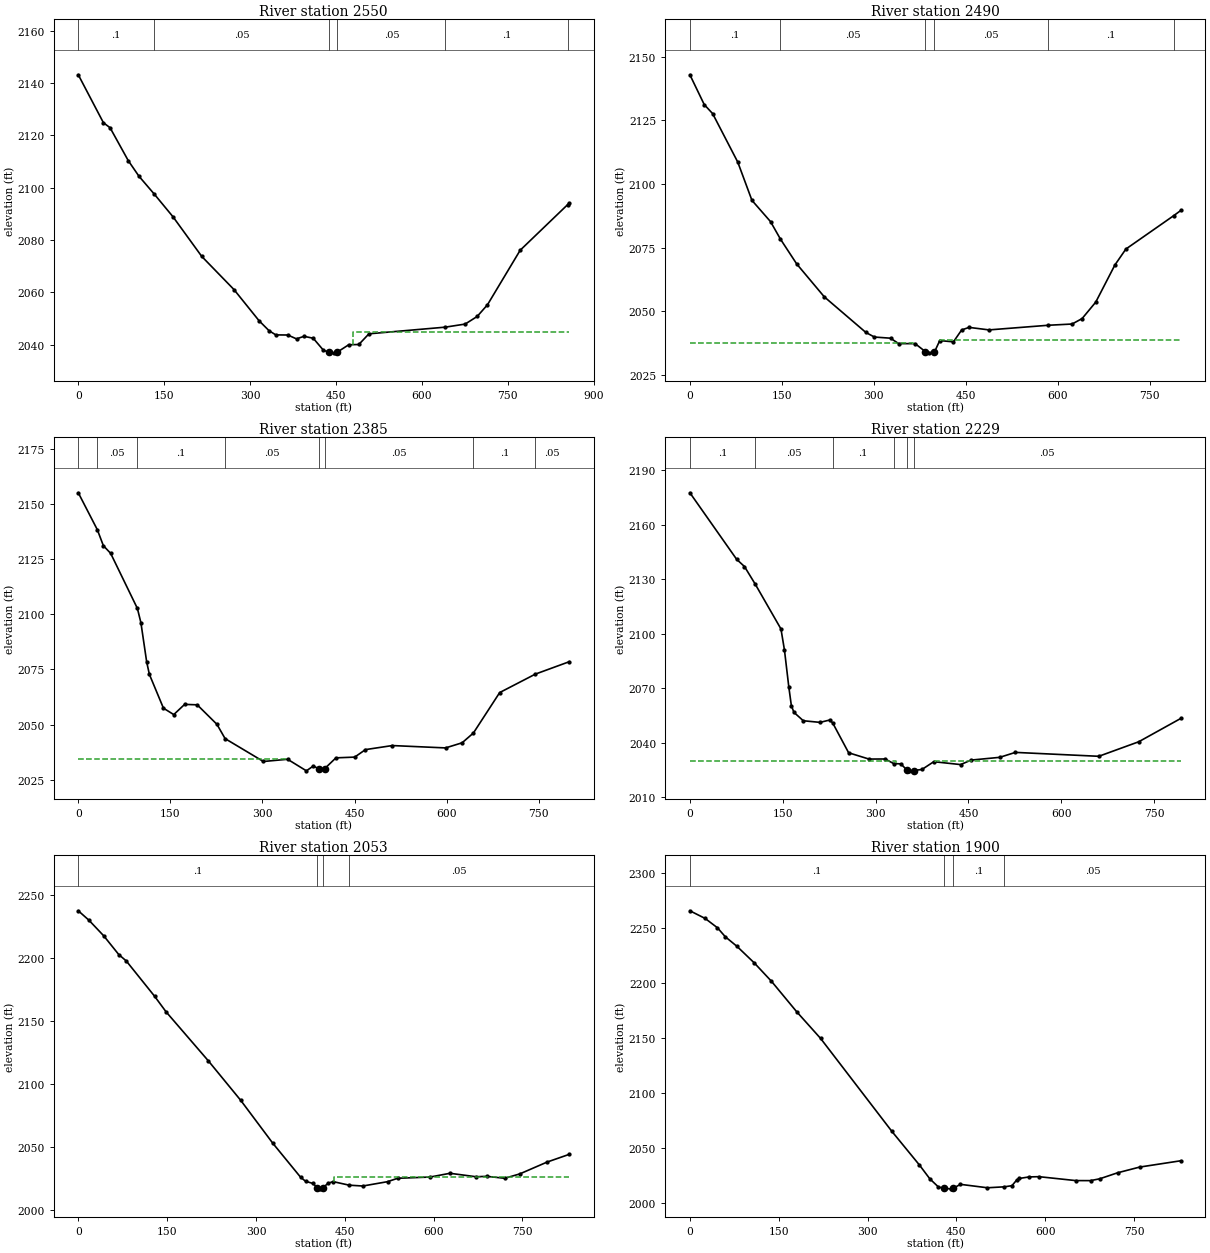
Type RM Length L Ch R = 1 ,2550    ,59.8,59.8,59.4
XS GIS Cut Line= 3
2418732.88992168576881.3649398242418549.12324593576598.116778129
2418327.00535531576128.482548231
#Sta/Elev= 30
       0 2143.19    43.9 2124.85    55.5 2122.94    87.3 2110.34   105.9  2104.4
  132.622097.568   165.4 2088.87   215.6 2073.71   271.8 2061.05   315.7  2049.1
   333.1  2045.3   344.9  2043.7   365.8 2043.66     381 2042.18   394.1 2043.16
   410.2 2042.42   427.9 2037.86   437.52037.037   445.6 2036.84   452.52037.156
   472.1 2039.92   489.8 2040.03   507.5 2044.12  640.912046.668   675.4 2047.84
   696.4 2050.75   714.4 2055.22   771.5 2076.08  854.482093.545   857.2 2094.02
#Mann= 6 ,-1 , 0
       0      .1       0  132.62     .05       0   437.5    .045       0
   452.5     .05       0  640.91      .1       0  854.48     .05       0
#XS Ineff= 2 , 0
             405    2037  479.21         2044.68
Permanent Ineff=
       F       F
Bank Sta=437.5,452.5
XS Rating Curve= 0 ,0
Exp/Cntr=0.5,0.3

Type RM Length L Ch R = 1 ,2490    ,105.5,105.1,105.6
XS GIS Cut Line= 3
2418762.81664691576811.1684408962418611.45235612576588.250121729
2418375.69100622576112.140625238
#Sta/Elev= 30
       0 2142.96    23.4 2131.24    37.1 2127.69    78.1 2108.61   101.2 2093.58
   131.5 2085.22  147.622078.359   174.2 2068.57   219.2 2055.63     287 2041.63
   300.9 2039.82   327.2 2039.37   340.5 2037.23   367.3 2037.23   383.82034.135
   389.6 2033.61   398.92033.956   407.5 2038.43   429.8 2037.93   443.2 2042.61
   455.3 2043.62   487.8 2042.63  584.422044.456   623.3 2044.94   639.6 2047.08
   661.9 2053.56   693.1 2068.15     711 2074.42  788.962087.542   800.7 2089.62
#Mann= 6 ,-1 , 0
       0      .1       0  147.62     .05       0   383.8    .045       0
   398.9     .05       0  584.42      .1       0  788.96     .05       0
#XS Ineff= 2 , 0
          363.39 2037.56  407.62         2038.54
Permanent Ineff=
       F       F
Bank Sta=383.8,398.9
XS Rating Curve= 0 ,0
Exp/Cntr(USF)=0,0
Exp/Cntr=0.5,0.3

Type RM Length L Ch R = 1 ,2385    ,156.3,156.6,157.5
XS GIS Cut Line= 3
2418827.65459429576773.529707422 2418702.7739927576550.721596322
2418482.94751092576052.887107577
#Sta/Elev= 30
       0 2155.14   30.962138.423    40.9 2131.12    52.7 2127.67   96.272102.664
     102  2096.2   111.4 2078.39   115.8 2072.76   138.7 2057.42   155.5 2054.51
   173.2 2059.14   193.7 2058.94   225.8  2050.1  239.122043.605   301.5 2033.23
   340.9 2034.24   371.5 2028.99   382.8 2031.19   391.9 2029.86     401 2029.92
   419.6 2034.88   450.2 2035.22   467.7 2038.62   511.4 2040.46   598.1 2039.39
   625.1 2041.71  643.472046.146   686.3  2064.5  744.432072.878   799.6  2078.5
#Mann= 8 ,-1 , 0
       0      .1       0   30.96     .05       0   96.27      .1       0
  239.12     .05       0   391.9    .045       0     401     .05       0
  643.47      .1       0  744.43     .05       0
#XS Ineff= 2 , 0
          341.16 2034.38
Permanent Ineff=
       F       F
Bank Sta=391.9,401
XS Rating Curve= 0 ,0
Exp/Cntr=0.3,0.1

Type RM Length L Ch R = 1 ,2229    ,176.2,176.2,176.1
XS GIS Cut Line= 2
2418909.77945317576764.336939632 2418663.8144938576010.405234956
#Sta/Elev= 30
       0 2177.66    75.5 2141.02    88.2 2137.02  105.452127.388   147.1 2102.65
   152.8 2090.92   159.7 2070.91   163.9 2060.38   168.1 2056.69   183.2 2052.08
   210.2 2051.19   225.8 2052.48  230.58 2050.92   256.4 2034.44   289.2 2030.98
   315.3 2031.02  329.392028.451   340.6 2028.34   350.82024.882   353.2 2024.49
   361.42024.667   374.8 2025.24   393.9 2029.52   437.3 2027.94   454.1 2030.41
   500.5 2031.93   525.7 2034.65   660.4  2032.5   724.9  2040.5     793 2053.38
#Mann= 6 ,-1 , 0
       0      .1       0  105.45     .05       0  230.58      .1       0
  329.39     .05       0   350.8    .045       0   361.4     .05       0
#XS Ineff= 2 , 0
          332.16 2030.15  395.41          2029.8
Permanent Ineff=
       F       F
Bank Sta=350.8,361.4
XS Rating Curve= 0 ,0
Exp/Cntr=0.3,0.1

Type RM Length L Ch R = 1 ,2053    ,151,152.3,153.3
XS GIS Cut Line= 2
     2419090.085      576765.491      2418833.93      575977.024
#Sta/Elev= 30
       0 2237.39    17.9 2229.95      43 2217.51    68.3 2202.71    81.1 2197.56
   128.7 2169.69   148.2 2157.26   219.7 2118.31   274.4 2086.97   328.6 2052.91
   375.3 2026.08   383.7 2022.86   396.3 2021.09   403.1  2017.9   408.9 2016.84
   413.2 2017.71   421.6 2021.22   430.2 2022.58  457.31 2019.75   480.4 2019.08
   522.3 2022.53   539.3 2025.23     594  2026.2   627.6 2029.17   671.4 2026.44
   689.8 2026.74   720.1 2025.22   745.4 2028.68   791.6 2038.08     829  2044.2
#Mann= 4 ,-1 , 0
       0      .1       0   403.1    .045       0   413.2      .1       0
  457.31     .05       0
#XS Ineff= 2 , 0
                          431.64         2026.52
Permanent Ineff=
       F       F
Bank Sta=403.1,413.2
XS Rating Curve= 0 ,0
Exp/Cntr=0.3,0.1

Type RM Length L Ch R = 1 ,1900    ,117.7,120.3,123.6
XS GIS Cut Line= 2
2419209.38593982576725.4717650442418991.93551769575925.320861505
#Sta/Elev= 30
       0 2265.57    25.9 2258.56    46.6 2250.09    59.8 2241.96    79.7 2233.15
   108.8 2218.14   137.8 2201.45   180.4 2173.75   220.7 2149.54   340.9 2065.16
   387.7 2034.39   405.3  2021.8   419.6 2014.51   428.5 2013.17   440.3 2012.74
   444.22013.077   456.9 2016.83   502.5 2013.71  531.052014.574   543.9 2015.61
   552.2 2020.92   556.4 2022.19   572.9 2023.58   589.5  2023.8   651.7 2020.24
   676.6 2020.21   692.1 2021.86   722.2 2027.31   759.5 2032.52   829.2 2038.28
#Mann= 4 ,-1 , 0
       0      .1       0   428.5    .045       0   444.2      .1       0
  531.05     .05       0
Bank Sta=428.5,444.2
XS Rating Curve= 0 ,0
Exp/Cntr=0.3,0.1

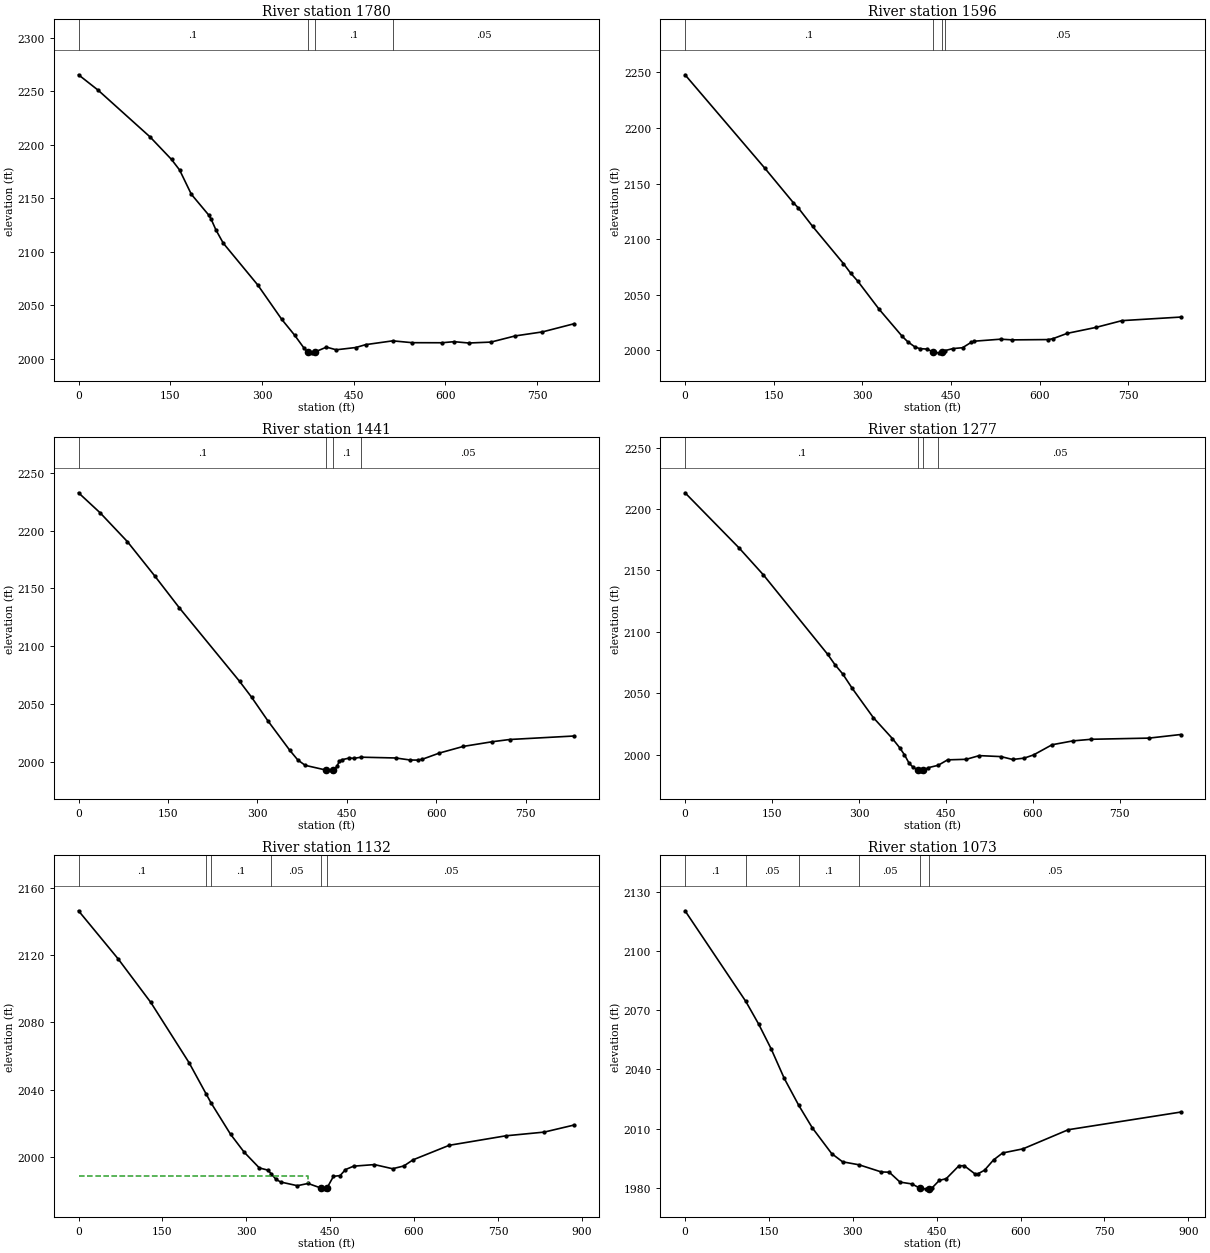
Type RM Length L Ch R = 1 ,1780    ,183.7,183.6,183.9
XS GIS Cut Line= 2
2419246.49969247      576704.3872419176.01437345575897.085921681
#Sta/Elev= 30
       0 2265.33      32 2250.97   116.9 2207.33   152.1 2186.22   165.3 2176.38
   184.5  2153.7   212.7 2134.45   216.7 2130.68   224.7 2120.41   236.7 2108.03
   293.1 2068.97   332.4 2036.81   353.2 2022.21   369.2 2009.65   375.12006.377
   381.3 2005.58   386.2 2006.26   405.4 2010.92   421.4 2008.43   453.5 2010.56
   469.6 2013.25  513.79 2016.78   545.9 2015.06   594.1    2015   614.1    2016
   638.2 2014.76   674.4 2015.62     714 2021.38   758.7 2025.15   810.4 2032.77
#Mann= 4 ,-1 , 0
       0      .1       0   375.1    .045       0   386.2      .1       0
  513.79     .05       0
Bank Sta=375.1,386.2
XS Rating Curve= 0 ,0
Exp/Cntr=0.3,0.1

Type RM Length L Ch R = 1 ,1596    ,150.7,155,158.5
XS GIS Cut Line= 3
2419362.53335531576698.399078319 2419401.5545734576385.008946262
2419341.49517478575866.078686725
#Sta/Elev= 30
       0 2247.81   134.9 2163.83     183 2132.91   191.3 2128.26   215.8 2111.47
   267.9 2078.06     280 2069.51   292.1 2062.26   328.3 2036.95   367.3 2012.63
   376.7 2007.75   388.7 2003.12   396.8 2001.61   408.9 2001.17   419.81998.623
   428.7 1997.79     4351998.582  439.231999.746   453.2 2001.62   469.3 2002.39
     484 2007.24   489.4 2008.27   533.7 2010.07   553.8 2009.44   614.2 2009.72
   622.3 2010.54   646.4 2015.31   694.7 2020.63     739 2026.75   838.2 2029.95
#Mann= 4 ,-1 , 0
       0      .1       0   419.8    .045       0     435      .1       0
  439.23     .05       0
Bank Sta=419.8,435
XS Rating Curve= 0 ,0
Exp/Cntr=0.3,0.1

Type RM Length L Ch R = 1 ,1441    ,163.8,164.8,164.8
XS GIS Cut Line= 3
     2419450.932      576699.9032419591.22054376576054.691806867
 2419497.4909876575912.220861505
#Sta/Elev= 30
       0 2232.75    36.2 2215.45    81.8 2190.58   127.4 2161.09   169.2 2133.13
   270.1 2069.62     290 2056.06   317.1 2035.78   354.1 2010.09   367.7 2001.63
     380 1997.05   415.61992.864     425 1992.28     4271992.851   429.1  1993.5
   433.2 1996.32   437.3 2000.43   441.4 2001.88   453.7 2003.31   461.9 2003.11
  473.832004.078   531.5 2003.41     556 2001.65   568.3 2001.57   576.5 2002.33
   605.1 2007.69   645.2 2013.42   693.7 2017.46   722.8 2019.38   830.8 2022.41
#Mann= 4 ,-1 , 0
       0      .1       0   415.6    .045       0     427      .1       0
  473.83     .05       0
Bank Sta=415.6,427
XS Rating Curve= 0 ,0
Exp/Cntr=0.3,0.1

Type RM Length L Ch R = 1 ,1277    ,151,144.1,134.5
XS GIS Cut Line= 3
     2419591.144      576734.6922419707.76309646576289.378120352
2419703.50201814575894.794921681
#Sta/Elev= 30
       0 2213.23    93.2 2168.33   135.1 2146.41   246.2  2081.6   258.6 2073.27
   271.9 2065.79   288.2 2054.12   324.7 2030.22   357.8 2013.04   370.2 2005.67
   378.5 1999.88   386.5 1993.03   392.7 1990.06   401.5 1987.36   406.2 1986.82
   411.1 1987.28   419.8 1989.42  436.681991.336   452.9 1995.77   485.1 1996.21
   507.5 1999.21   545.1 1998.41   565.1 1996.07   585.1 1997.18   601.1 1999.76
   633.1 2008.06   669.1 2011.21   700.8 2012.52   800.4 2013.47   854.9 2016.39
#Mann= 4 ,-1 , 0
       0      .1       0   401.5    .045       0   411.1      .1       0
  436.68     .05       0
Bank Sta=401.5,411.1
XS Rating Curve= 0 ,0
Exp/Cntr=0.3,0.1

Type RM Length L Ch R = 1 ,1132    ,60,59.8,59.5
XS GIS Cut Line= 4
2419791.10100758 576712.498134852419885.03913101576394.536358101
2419793.61391776576255.1970622792419733.55440582575871.841393697
#Sta/Elev= 30
       0 2146.27    70.9  2117.7   129.3 2091.82   197.8 2055.99  227.81 2037.73
  236.862032.253   271.8 2013.58   296.1 2002.95   323.3 1993.56   338.7 1992.23
  344.631990.049   353.3  1986.7     362 1985.14   391.3    1983   410.5 1984.32
   434.4  1981.5     440 1981.13   443.9  1981.4   455.9 1988.54   467.9 1989.02
   477.4 1992.58     492  1994.6   529.2 1995.53   561.6 1993.07   581.8 1994.72
     598 1998.33   662.8 2006.98     764 2012.62   832.8 2014.83   886.2 2019.03
#Mann= 6 ,-1 , 0
       0      .1       0  227.81     .05       0  236.86      .1       0
  344.63     .05       0   434.4    .045       0   443.9     .05       0
#XS Ineff= 2 , 0
          410.57  1988.6
Permanent Ineff=
       F       F
Bank Sta=434.4,443.9
XS Rating Curve= 0 ,0
Exp/Cntr(USF)=0,0
Exp/Cntr=0.5,0.3

Type RM Length L Ch R = 1 ,1073    ,70.2,70.2,70
XS GIS Cut Line= 4
2419837.24162358576674.7467217582419931.17974701576356.784945009
2419839.75453376576217.4456491872419779.69502182575834.089980605
#Sta/Elev= 30
       0 2120.44  108.722074.442   131.6 2062.98   153.9 2050.45   177.5 2035.38
  203.432021.703   227.5 2010.37   262.2 1997.28   281.7 1993.11   311.31991.585
   350.7 1987.99   365.2 1987.83   384.4 1982.82   405.6 1981.89   420.51979.649
   430.6  1979.4   436.21979.518   441.8 1979.91   454.7 1983.68   467.1 1984.57
   489.7 1991.08   499.1 1991.15   519.3 1986.79   523.4 1986.97   535.5 1988.84
   551.7 1994.08   567.9 1997.59   604.3 1999.69   685.3 2009.39   886.2 2018.33
#Mann= 6 ,-1 , 0
       0      .1       0  108.72     .05       0  203.43      .1       0
   311.3     .05       0   420.5    .045       0   436.2     .05       0
#XS Ineff= 2 , 0
             410    1979     480            1979
Permanent Ineff=
       F       F
Bank Sta=420.5,436.2
XS Rating Curve= 0 ,0
Exp/Cntr(USF)=0,0
Exp/Cntr=0.5,0.3

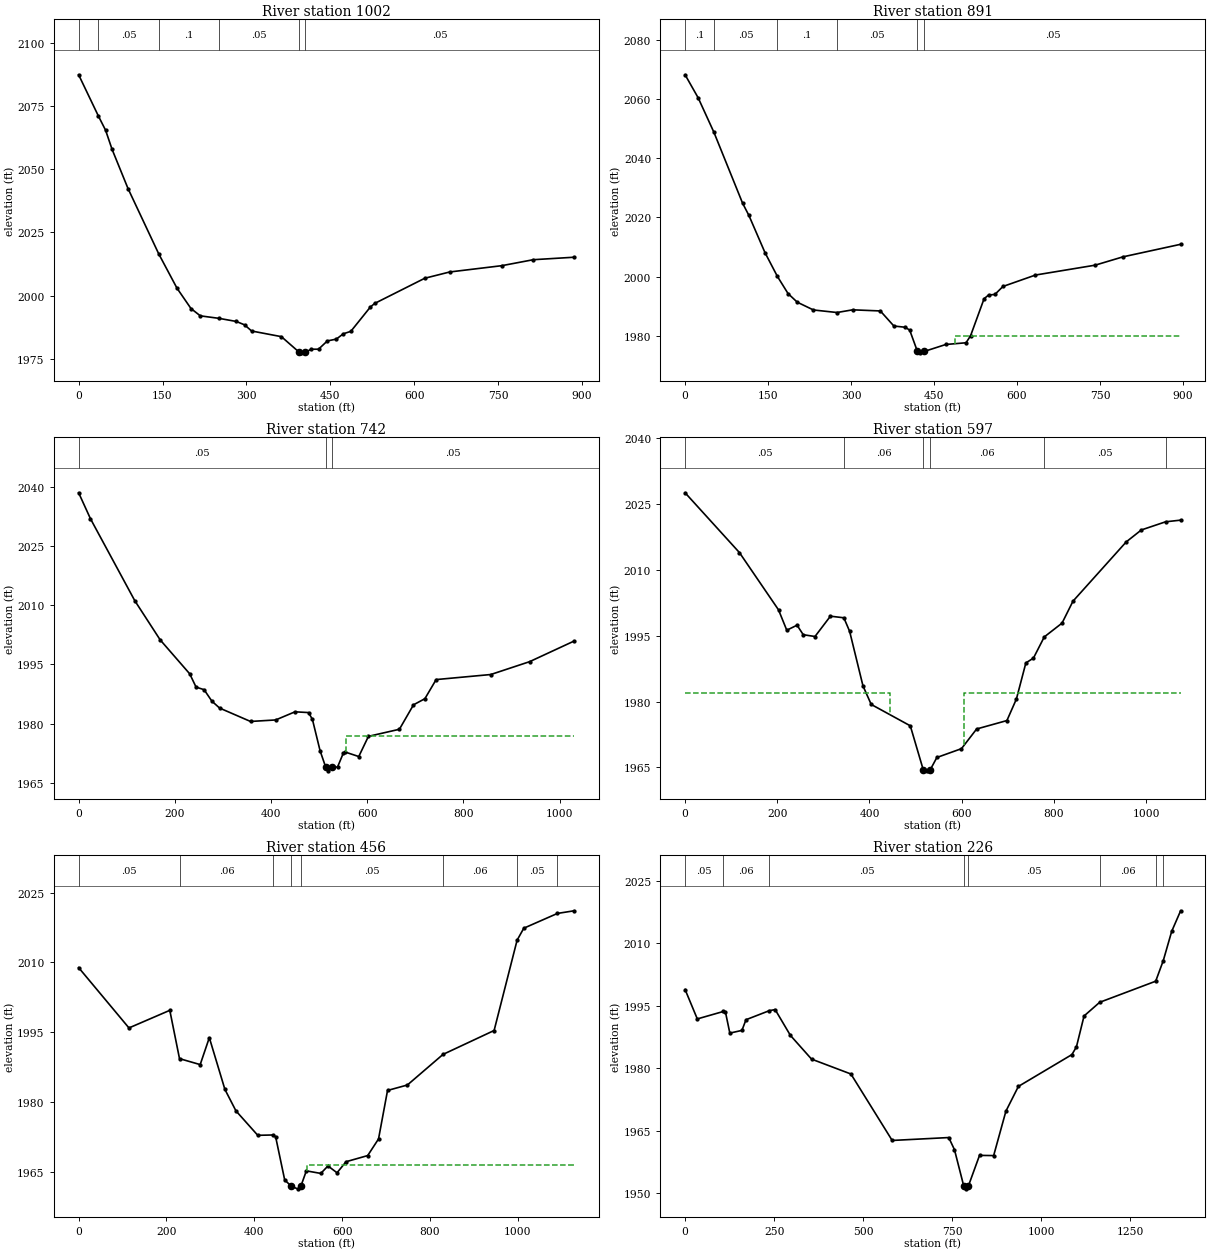
Type RM Length L Ch R = 1 ,1002    ,107.8,111,115.8
XS GIS Cut Line= 4
2419879.18763813576613.2259004232419973.12576155576295.264123674
2419881.70054831576155.9248278522419821.64103637 575772.56915927
#Sta/Elev= 30
       0 2087.32   35.452070.958    48.2 2065.39    59.8 2057.83    88.3 2042.33
  143.32 2016.45   175.9 2002.91   200.9 1994.87   217.6 1991.97  251.191990.976
     282 1989.75   296.8 1988.41   309.3 1985.98   362.6 1983.74   394.4 1977.59
   397.3 1977.34   405.11977.547   416.1 1978.77     429 1978.78   444.8 1982.05
   460.8 1982.77   473.5 1984.89   486.8 1985.84   521.8 1995.48   529.6  1996.9
     619 2006.84   663.5 2009.32   756.6 2011.81   813.2 2014.18   886.2 2015.16
#Mann= 6 ,-1 , 0
       0      .1       0   35.45     .05       0  143.32      .1       0
  251.19     .05       0   394.4    .045       0   405.1     .05       0
Bank Sta=394.4,405.1
XS Rating Curve= 0 ,0
Exp/Cntr=0.5,0.3

Type RM Length L Ch R = 1 ,891     ,149,149.9,150.9
XS GIS Cut Line= 4
2419954.42295091576623.1521349542420055.30509147576279.605023722
2420016.79865011576081.4101049892419859.78168165 575784.64167537
#Sta/Elev= 30
       0 2068.11    23.6 2060.34   52.092048.702   103.9 2024.77   115.3 2020.64
   144.5 2008.04  166.812000.058   186.1 1994.25   202.8 1991.34     232 1988.72
   274.61987.861   302.9 1988.77   352.9 1988.39   377.4  1983.3   397.8 1982.89
     406 1981.91   419.4    1975   424.2 1974.25   432.51974.735   471.2 1977.07
   507.8 1977.65     516 1980.02   540.4 1992.51   548.6 1993.78   559.9 1993.95
   574.5 1996.65   633.3 2000.51   741.1 2003.84   791.4 2006.65   895.7 2010.89
#Mann= 6 ,-1 , 0
       0      .1       0   52.09     .05       0  166.81      .1       0
   274.6     .05       0   419.4    .045       0   432.5     .05       0
#XS Ineff= 2 , 0
                          488.19         1979.98
Permanent Ineff=
       F       F
Bank Sta=419.4,432.5
XS Rating Curve= 0 ,0
Exp/Cntr=0.3,0.1

Type RM Length L Ch R = 1 ,742     ,147.4,144.3,143.3
XS GIS Cut Line= 4
 2420114.5200376576710.9172161162420218.70608873576481.234330659
2420173.71665756576036.0757485362419979.76319085575768.088057252
#Sta/Elev= 30
       0 2038.45    24.6 2031.88   116.8 2011.13   169.5 2001.23     231 1992.62
   244.2 1989.26   260.9 1988.61     277 1985.72   293.1 1983.96   357.4 1980.57
   409.7 1980.95   449.9 1983.01     478 1982.82   486.1  1981.1   502.1 1973.14
   513.61969.051   518.2 1968.07   527.8 1969.04   538.3 1969.02   550.3 1972.52
   554.4 1972.82   582.5 1971.69   602.6  1976.8     667 1978.59   696.3 1984.78
     720 1986.33   743.4 1991.17     857 1992.45   937.7  1995.7  1030.4 2000.93
#Mann= 3 ,-1 , 0
       0     .05       0   513.6    .045       0   527.8     .05       0
#XS Ineff= 2 , 0
                          555.22         1976.98
Permanent Ineff=
       F       F
Bank Sta=513.6,527.8
XS Rating Curve= 0 ,0
Exp/Cntr(USF)=0,0
Exp/Cntr=0.5,0.3

Type RM Length L Ch R = 1 ,597     ,141.7,141.2,140.5
XS GIS Cut Line= 4
2420228.64974752576714.1421532572420377.82522983576413.423323844
2420276.00704349575982.4719305122420138.67088518575719.638937876
#Sta/Elev= 30
       0 2027.54   117.9 2013.92   202.7 2000.88   220.6 1996.24   242.9 1997.39
   256.3 1995.22   281.8 1994.81   315.3 1999.44  344.421999.072     357 1995.98
   385.9 1983.57   403.8 1979.34   488.6 1974.47   516.51964.524   525.6 1964.22
   531.6 1964.41   546.2 1967.26   599.6 1969.27   632.5 1973.75   698.2 1975.67
   718.8 1980.58   739.3 1988.79   755.8  1989.9  779.241994.713   817.8 1997.86
   841.5 2002.85   957.1 2016.36   989.8 2019.07 1042.452020.931  1075.1 2021.31
#Mann= 6 ,-1 , 0
       0     .05       0  344.42     .06       0   516.5    .045       0
   531.6     .06       0  779.24     .05       0 1042.45     .06       0
#XS Ineff= 2 , 0
             445    1982     605            1982
Permanent Ineff=
       F       F
Bank Sta=516.5,531.6
XS Rating Curve= 0 ,0
Exp/Cntr(USF)=0,0
Exp/Cntr=0.5,0.3

Type RM Length L Ch R = 1 ,456     ,239.6,230.2,222.2
XS GIS Cut Line= 4
2420356.51444664576695.1992348692420505.68992895576394.480405456
2420403.87174261575963.5290121242420155.24593877575717.271073077
#Sta/Elev= 30
       0 2008.89   114.6 1995.94   207.6 1999.72   229.71989.349   276.8 1988.07
   297.6 1993.85   333.1 1982.74   358.2 1978.14   407.9 1972.89  443.161972.964
   448.6 1972.57   469.2 1963.32   484.3 1961.95   498.5  1961.4   506.2    1962
   518.5 1965.26   551.4 1964.71   567.8 1966.31   588.4 1964.85   608.9 1967.22
   658.2 1968.54   682.9 1972.11   703.4 1982.52   748.6 1983.69  829.741990.258
   946.1 1995.39  998.452014.778  1013.7 2017.35 1090.312020.523  1128.4 2021.09
#Mann= 8 ,-1 , 0
       0     .05       0   229.7     .06       0  443.16     .05       0
   484.3    .045       0   506.2     .05       0  829.74     .06       0
  998.45     .05       0 1090.31     .06       0
#XS Ineff= 2 , 0
                          520.24         1966.49
Permanent Ineff=
       F       F
Bank Sta=484.3,506.2
XS Rating Curve= 0 ,0
Exp/Cntr(USF)=0,0
Exp/Cntr=0.5,0.3

Type RM Length L Ch R = 1 ,226     ,130.6,128.4,126.1
XS GIS Cut Line= 3
2420406.23960741576683.3599108762420789.83370477 576242.93705835
2420186.02818115575705.431749085
#Sta/Elev= 30
       0 1998.92    34.3 1991.85  107.571993.646   113.5 1993.46   125.7 1988.44
   159.7 1989.09   171.1 1991.66  236.721993.839     253  1994.1   295.8  1987.9
   355.3 1982.18   465.9  1978.6   581.9 1962.61   740.8 1963.31   756.9 1960.39
   782.71951.736     789 1950.97   796.31951.725   827.3 1959.02     867 1958.97
   901.5 1969.67   936.5 1975.61  1086.9 1983.27  1099.6 1985.13    1121 1992.56
 1164.881995.846 1322.312000.927 1343.66 2005.89  1367.3 2012.93  1392.4 2017.87
#Mann= 8 ,-1 , 0
       0     .05       0  107.57     .06       0  236.72     .05       0
   782.7    .045       0   796.3     .05       0 1164.88     .06       0
 1322.31     .05       0 1343.66     .06       0
Bank Sta=782.7,796.3
XS Rating Curve= 0 ,0
Exp/Cntr(USF)=0,0
Exp/Cntr=0.3,0.1

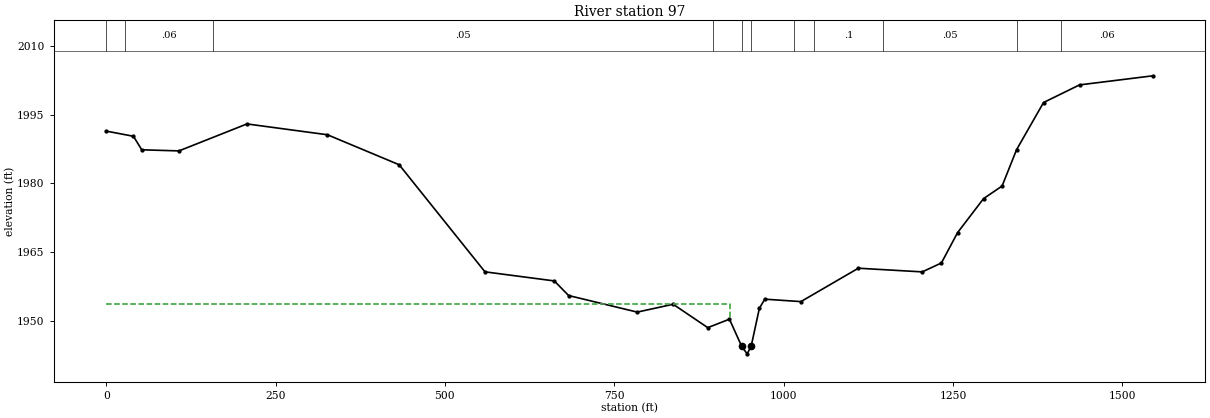
Type RM Length L Ch R = 1 ,97      ,,,
XS GIS Cut Line= 4
2420468.38185119576681.6337374382420915.65555742576165.831058325
2420820.25466124576072.1761658562420201.56374209575686.443841265
#Sta/Elev= 30
       0 1991.39    40.2 1990.26    52.5 1987.31   107.4 1987.07   207.8 1992.95
   326.6 1990.59   432.5 1984.05   559.2  1960.7   661.5 1958.72   682.7 1955.53
     784 1951.92     837 1953.63   888.1 1948.53   920.1 1950.38   938.21944.443
   946.2 1942.82   952.11944.428   964.3 1952.76   972.3 1954.74  1025.6 1954.21
  1110.4 1961.49  1204.7 1960.69    1233 1962.63  1256.9 1969.25  1295.2 1976.66
  1322.6 1979.41    1344 1987.34  1383.8 1997.62  1436.9 2001.46  1545.5 2003.45
#Mann= 11 ,-1 , 0
       0     .05       0   27.51     .06       0  156.98     .05       0
  895.68      .1       0   938.2    .045       0   952.1      .1       0
 1014.77     .05       0 1045.15      .1       0 1146.59     .05       0
 1344.09      .1       0 1410.21     .06       0
#XS Ineff= 2 , 0
           920.3 1953.75
Permanent Ineff=
       F       F
Bank Sta=938.2,952.1
XS Rating Curve= 0 ,0
Exp/Cntr(USF)=0,0
Exp/Cntr=0.3,0.1
LCMann Table=0

Chan Stop Cuts=-1
Use User Specified Reach Order=0
Composite Channel Slope=5